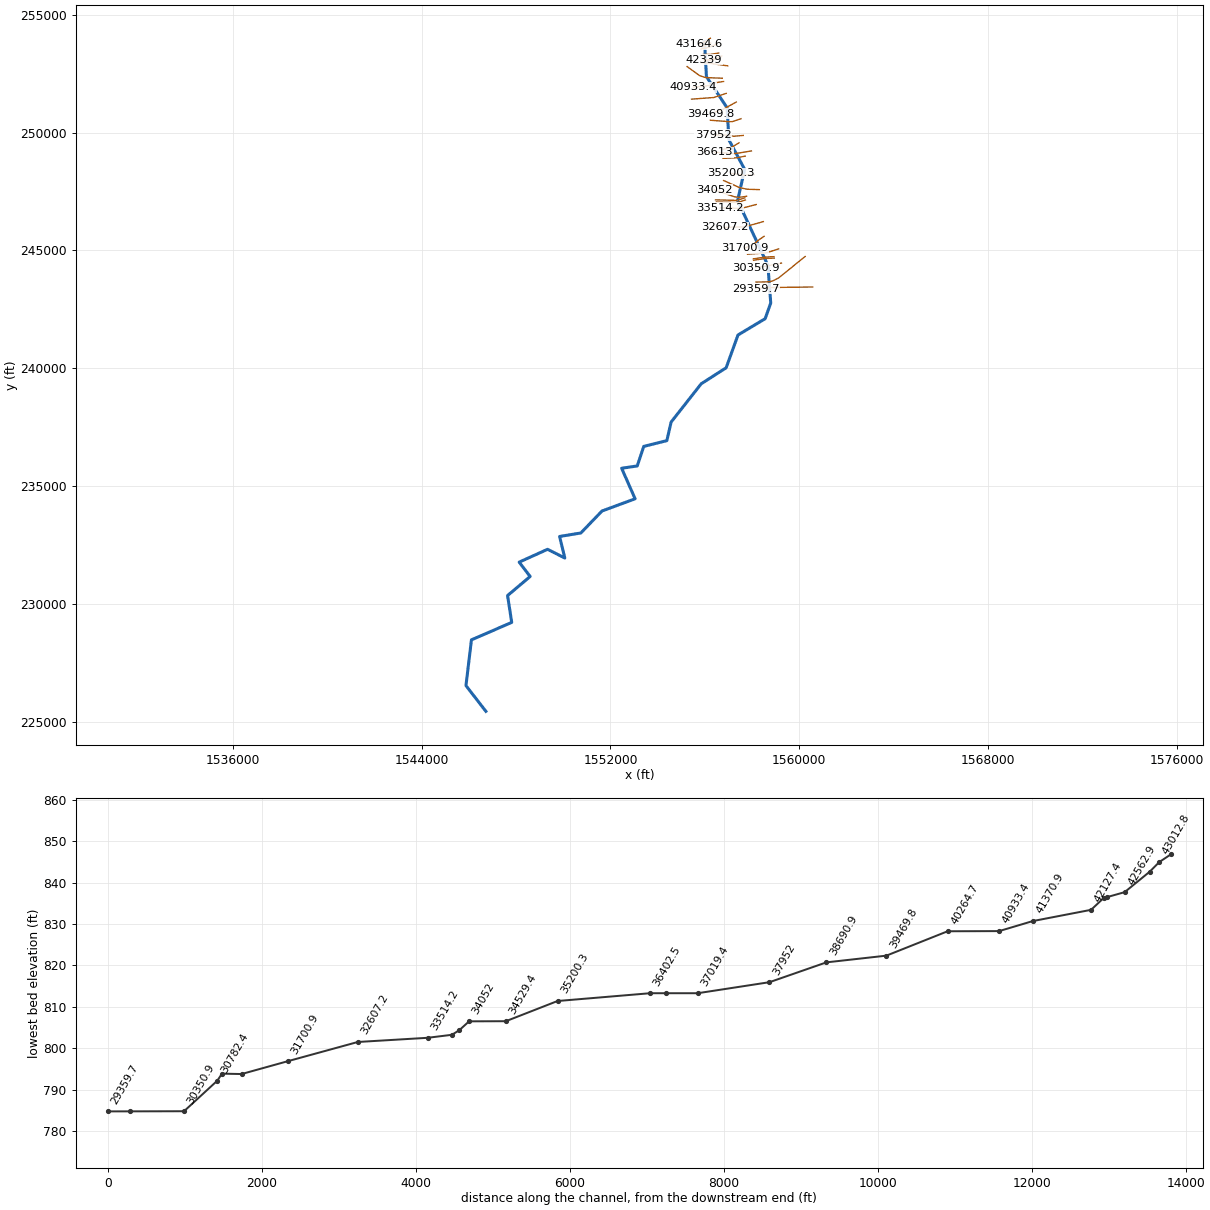
--- SLBCR.prj (project) ---

Proj Title=SLBCR
Current Plan=p01
Default Exp/Contr=0,0
English Units
Geom File=g01
Flow File=f01
Plan File=p01
BEGIN DESCRIPTION:
END DESCRIPTION:
DSS Export Rating Curves= 0
DSS Export Rating Curve Sorted= 0
DSS Export Volume Flow Curves= 0
DXF OffsetX= 0
DXF OffsetY= 0
DXF ScaleX= 0
DXF ScaleY= 0

--- SLBCR.p01 (plan) ---

Plan Title=Floodplain
Program Version=4.00
Geom File=g01
Flow File=f01
K Sum by GR=0
Std Step Tol=0.01
Critical Tol=0.01
Num of Std Step Trials=20
Max Error Tol=0.3
Flow Tol Ratio=0.001
Split Flow NTrial=30
Split Flow Tol=0.02
Split Flow Ratio=0.02
Log Output Level=0
Friction Slope Method=1
Unsteady Friction Slope Method=2
Unsteady Bridges Friction Slope Method=1
Global Log Level=0
CheckData=False
Run HTab=0
Run UNet=0
Run PostProcess=0
UNET Theta=0
UNET Theta Warmup=0
UNET ZTol=0
UNET ZSATol=0
UNET MxIter=0
UNET MaxInSteps=0
UNET DtIC=0
UNET DtMin=0
UNET MaxCRTS=0
UNET WFStab=0
UNET SFStab=0
UNET WFX=0
UNET SFX=0
UNET DSS MLevel=0
UNET DZMax Abort=0
UNET Convert EG Bridges=0
UNET Use Existing IB Tables=0
UNET Froude Limit=0
UNET Froude Power=0
Write IC File=0
Echo Input=False
Echo Output=False
Write Detailed=0

--- SLBCR.f01 (steady flow) ---

Flow Title=NFF Regression Equation
Program Version=4.10
Number of Profiles= 1
Profile Names=P100yr
River Rch & RM=SLBCR,Main            ,43164.6
517.6364
River Rch & RM=SLBCR,Main            ,42339
528.7188
River Rch & RM=SLBCR,Main            ,42127.4
751.2084
River Rch & RM=SLBCR,Main            ,41370.9
756.4746
River Rch & RM=SLBCR,Main            ,40933.4
1017.205
River Rch & RM=SLBCR,Main            ,38690.9
1096.251
River Rch & RM=SLBCR,Main            ,34529.4
1188.122
River Rch & RM=SLBCR,Main            ,33514.2
1322.368
River Rch & RM=SLBCR,Main            ,29643.5
1406.239
River Rch & RM=SLBCR,Main            ,29359.7
1733.986
River Rch & RM=SLBCR,Main            ,26644.4
1778.256
River Rch & RM=SLBCR,Main            ,25485
1999.221
River Rch & RM=SLBCR,Main            ,21486.3
 2094.14
River Rch & RM=SLBCR,Main            ,20377.7
2521.267
River Rch & RM=SLBCR,Main            ,12154.7
2672.559
River Rch & RM=SLBCR,Main            ,11085.3
3002.625
River Rch & RM=SLBCR,Main            ,445.6
3185.781
Boundary for River Rch & Prof#=SLBCR,Main            , 1
Up Type= 0
Dn Type= 3
Dn Slope=0.00083
DSS Import GetInterval= 0
DSS Import GetPeak= 0
DSS Import FillOption= 0

--- SLBCR.g01 (geometry) ---

Geom Title=USGS 10m DEM
Program Version=4.10

River Reach=SLBCR           ,Main
Reach XY= 30
     1555983.967      253865.622      1556064.78      252375.962
       1556938.5      251056.727     1557017.818       249688.67
     1557684.012      248440.112     1557385.213      247120.356
     1558669.524      244361.898     1558787.975      242767.644
     1558551.627      242102.289     1557401.551       241411.24
     1556899.113      240017.874     1555842.421      239338.231
     1554568.823      237715.123     1554387.234      236926.112
     1553409.141      236681.033     1553133.078      235852.166
     1552472.562      235752.658     1553042.911      234457.976
     1551641.426      233939.334     1550743.792      233005.987
     1549843.964      232857.892     1550065.941      231942.836
     1549335.223      232313.722     1548132.257       231768.32
     1548596.334      231158.862     1547639.892      230349.638
     1547815.965      229210.419      1546109.89      228468.956
     1545877.939      226526.808     1546722.038      225434.205

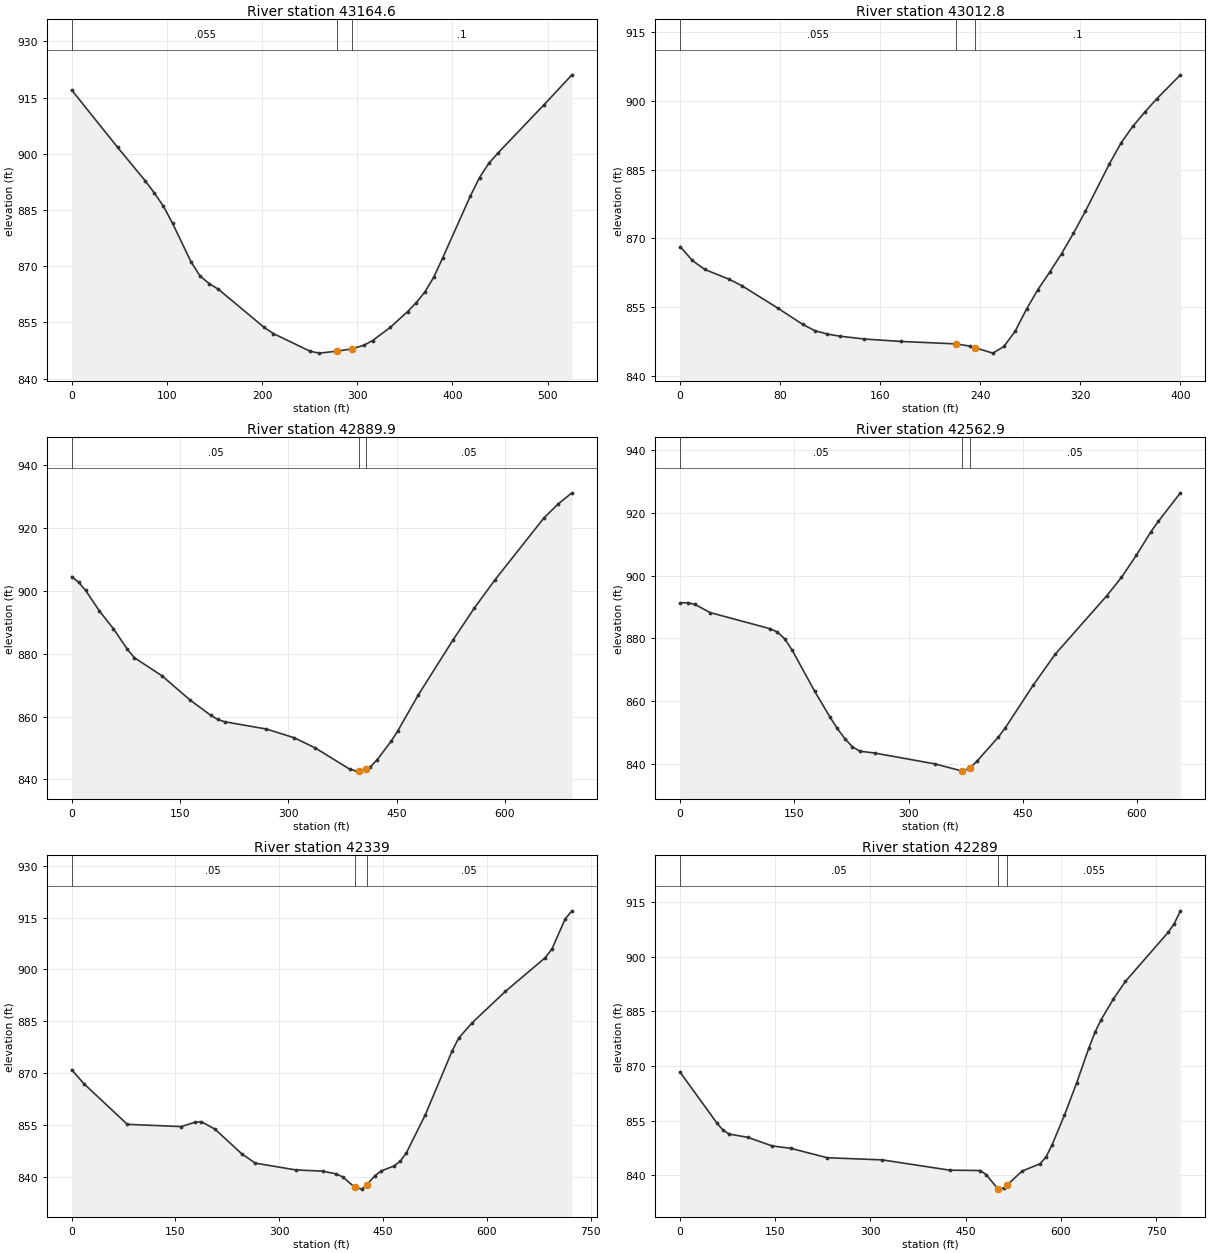
Type RM Length L Ch R = 1 ,43164.6 ,151.1,151.8,154.2
XS GIS Cut Line= 4
     1556230.503      254007.553     1555994.392      253858.247
     1555895.434      253809.636      1555772.17      253752.344
#Sta/Elev= 30
       0     917    48.2  901.72    77.1  892.83    86.7  889.58    96.3  886.02
     106  881.42   125.2  871.23   134.9  867.34   144.5  865.35   154.1  863.84
   202.3  853.64   211.9  852.01   250.5   847.3   260.1   846.8   279.1  847.33
   294.1  847.94   306.9  848.89   316.1  850.16   334.5  853.64   352.9  857.89
     362  860.29   371.2  863.17   380.4   867.1   389.6  872.15   418.7  888.66
   428.4  893.65   438.2  897.45   447.9  900.22   496.4  913.13   525.5  921.05
#Mann= 3 , 0 , 0
       0    .055       0   279.1    .045       0   294.1      .1       0
Bank Sta=279.1,294.1
XS Rating Curve= 0 ,0
Exp/Cntr=0.3,0.1

Type RM Length L Ch R = 1 ,43012.8 ,131.1,122.9,115.5
XS GIS Cut Line= 4
     1556245.011      253800.943      1556062.72      253728.243
     1555986.765        253680.5     1555880.428      253639.268
#Sta/Elev= 30
       0  868.19     9.8  865.15    19.6  863.21    39.2  861.05    49.1  859.69
    78.5  854.69    98.1  851.18   107.9  849.82   117.8  849.09   127.6  848.63
   147.2  848.01   176.6  847.48   220.6  846.95   232.1  846.44   235.6  846.12
   250.1  844.93     259  846.41     268  849.78     277  854.56     286  858.78
   295.5  862.61     305  866.66   314.5   871.1     324  875.88     343  886.13
   352.5  890.79     362  894.46   371.5  897.53     381  900.42     400  905.68
#Mann= 3 , 0 , 0
       0    .055       0   220.6    .045       0   235.6      .1       0
Bank Sta=220.6,235.6
XS Rating Curve= 0 ,0
Exp/Cntr=0.3,0.1

Type RM Length L Ch R = 1 ,42889.9 ,331.5,327.1,320.3
XS GIS Cut Line= 4
     1556496.996      253746.268     1556160.191      253629.948
     1556031.718       253593.49     1555833.802      253548.351
#Sta/Elev= 30
       0  904.51     9.6  902.74    19.3  900.14    38.5  893.57    57.8  887.96
      77  881.44    86.7  878.74   125.2  872.95   163.7   865.3   192.6   860.4
   202.2  859.08   211.9  858.34   269.6  856.03   308.2  853.25   337.1  850.04
   384.9  843.28   394.5  842.63   398.3  842.69  408.16843.2933   413.6  843.98
   423.1  846.24   442.2  852.07   451.7  855.45   480.3  866.96   528.5  884.49
   557.5  894.45   586.5  903.57   654.2  923.22   673.5  927.58   692.9  931.19
#Mann= 3 , 0 , 0
       0     .05       0   398.3    .045       0  408.16     .05       0
Bank Sta=398.3,408.16
XS Rating Curve= 0 ,0
Exp/Cntr=0.3,0.1

Type RM Length L Ch R = 1 ,42562.9 ,216.9,223.8,231
XS GIS Cut Line= 4
      1556589.01      253379.948     1556259.149      253326.129
      1556120.26      253320.921     1555936.232      253320.921
#Sta/Elev= 30
       0  891.37     9.8  891.39    19.7  890.84    39.3  888.26     118  883.11
   127.8  882.04   137.6  879.82   147.4  876.16   176.9  863.08   196.6  855.02
   206.4   851.3   216.3  848.05   226.1  845.49   235.9  844.05   255.6  843.44
   334.2     840  370.68 837.698   371.3  837.67   380.6   838.6   389.8  840.82
   417.6  848.41   426.9  851.39   463.9  865.11   492.6  874.93   560.4   893.6
   579.8  899.48   599.1  906.47   618.5  914.04   628.2  917.36   657.2  926.45
#Mann= 3 , 0 , 0
       0     .05       0  370.68    .045       0   380.6     .05       0
Bank Sta=370.68,380.6
XS Rating Curve= 0 ,0
Exp/Cntr=0.3,0.1

Type RM Length L Ch R = 1 ,42339   ,49.4,50.1,49.1
XS GIS Cut Line= 5
     1556646.996      253248.655     1556589.705      253192.231
     1556273.732       253134.94     1556171.302      253095.921
     1555959.496      253095.921
#Sta/Elev= 30
       0  871.01    17.9  866.94    80.4  855.23   158.3  854.58   177.7   855.8
   187.4     856   206.9  853.87   245.8  846.71   265.3  844.02   323.7  842.06
   362.6  841.69   382.1  840.92   391.8  840.02  408.78837.1135   419.8   836.5
  426.13837.6664   438.1  840.36   447.2  841.73   465.5  843.18   474.6  844.49
   483.7  846.99   511.2  858.04   549.7  876.38   559.3  880.16   578.5  884.53
   626.7  893.64   684.4  903.41   694.1  905.94   713.3  914.63     723  916.95
#Mann= 3 , 0 , 0
       0     .05       0  408.78    .045       0  426.13     .05       0
Bank Sta=408.78,426.13
XS Rating Curve= 0 ,0
Exp/Cntr=0.3,0.1

Type RM Length L Ch R = 1 ,42289   ,173.1,161.5,148.6
XS GIS Cut Line= 5
     1556712.274      253253.212     1556625.468      253136.893
     1556300.685      253091.971     1556201.857      253060.504
     1555990.052      253060.504
#Sta/Elev= 30
       0  868.29    58.1  854.32    67.7  852.38    77.4  851.33   106.4  850.45
   145.1  848.08   174.1  847.43   231.9  844.84   318.7  844.25   424.8  841.43
     473  841.33   482.4  840.21  500.72836.3367   501.3  836.23   510.7  836.56
  514.71837.2497     539  841.18   567.3  843.19   576.7  845.05   586.4  848.45
   605.6  856.46   624.9  865.32   644.1  874.89   653.8  879.24   663.4  882.66
   682.6   888.3   701.9  893.22   769.3  906.67   778.9  909.08   788.5  912.56
#Mann= 3 , 0 , 0
       0     .05       0  500.72    .045       0  514.71    .055       0
Bank Sta=500.72,514.71
XS Rating Curve= 0 ,0
Exp/Cntr=0.3,0.1

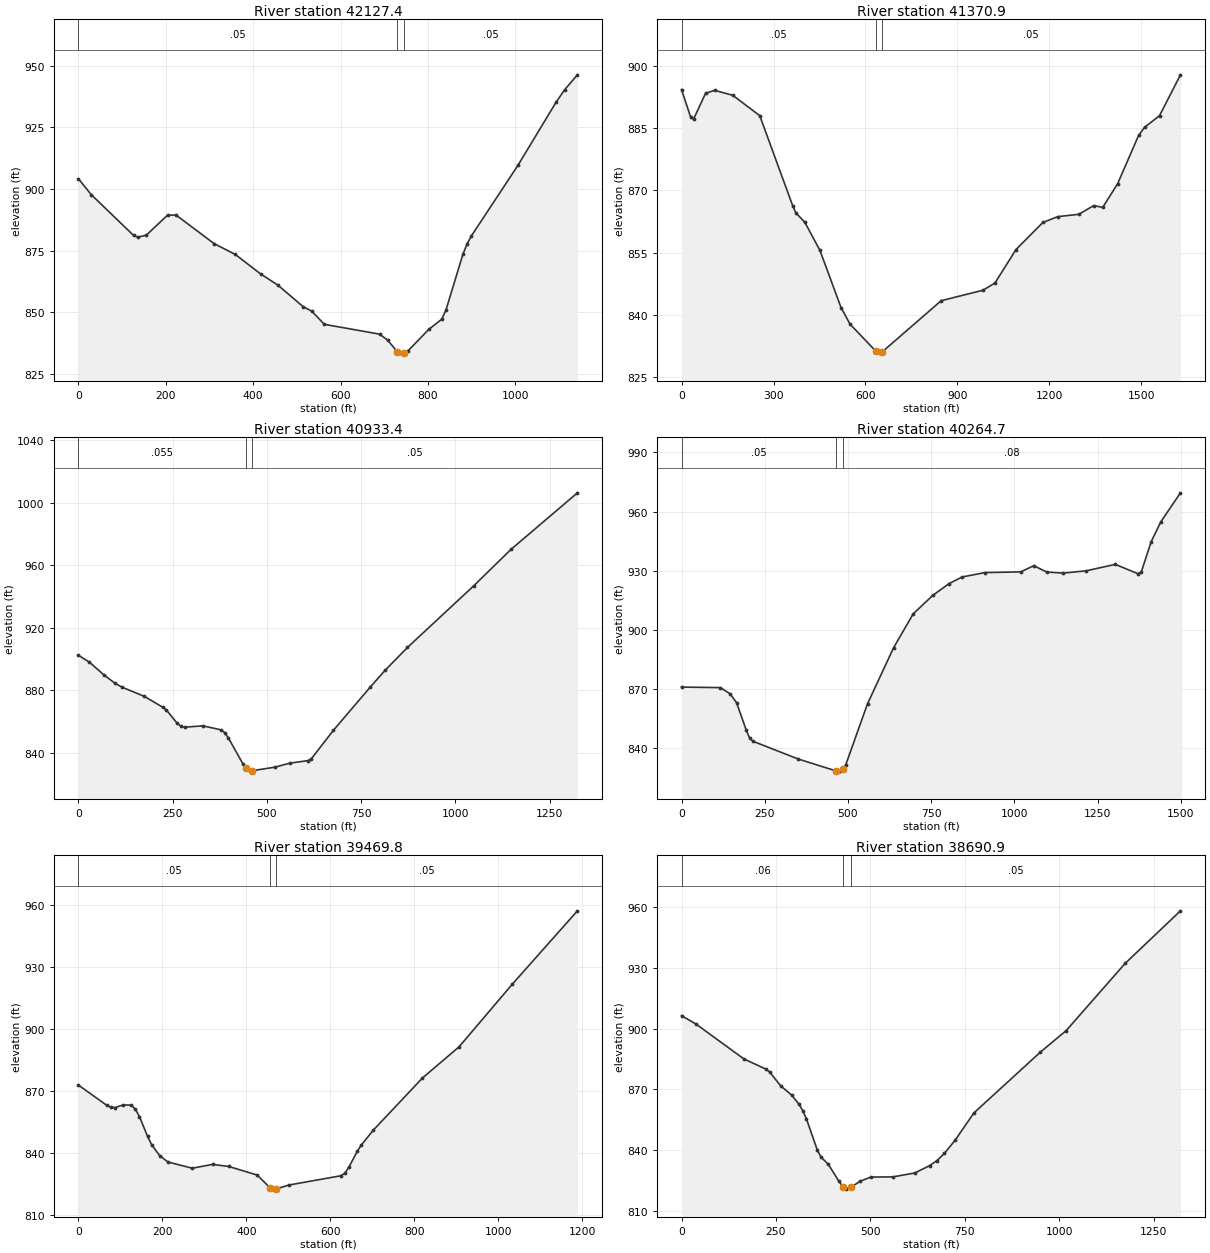
Type RM Length L Ch R = 1 ,42127.4 ,733.7,756.6,759.4
XS GIS Cut Line= 4
     1556967.482      252835.616      1556285.19       252931.97
     1556182.921      252947.662     1555834.669      252978.845
#Sta/Elev= 30
       0  904.15    29.1  897.74   126.2  881.17   135.9  880.48   155.3  881.28
   203.8  889.39   223.2  889.45   310.6  877.84   359.1  873.44   417.3   865.5
   456.1  861.06   514.4  852.24   533.8  850.48   562.9  845.09   689.1  841.12
   707.9  838.66   729.6  834.01   736.1  833.41   744.6  833.51   754.9  834.44
   802.2   843.1   831.4  847.13   841.1  850.83   879.9  873.45   889.6  877.74
   899.4  880.96  1006.2  909.68  1093.6  935.32    1113  940.32  1142.2  946.35
#Mann= 3 , 0 , 0
       0     .05       0   729.6     .04       0   744.6     .05       0
Bank Sta=729.6,744.6
XS Rating Curve= 0 ,0
Exp/Cntr=0.3,0.1

Type RM Length L Ch R = 1 ,41370.9 ,426.2,437.5,440.9
XS GIS Cut Line= 5
     1556736.579       252311.31     1556128.378        252332.5
     1555979.073      252349.861     1555767.829      252425.893
     1555246.996      252804.366
#Sta/Elev= 30
       0  894.37    29.4  887.79    39.3  887.22    78.5  893.46     108  894.17
   166.9  892.99   255.2  888.05   363.2  866.17     373  864.59   402.4  862.27
   451.5   855.5   520.2  841.71   549.7   837.7  634.52831.1043   646.2   830.7
   653.3  830.92   846.7  843.36   983.4   845.9  1022.4  847.65  1090.7  855.71
  1178.5  862.26  1227.3  863.67  1295.6  864.23  1344.3  866.34  1373.6   865.9
  1422.4  871.64  1490.6  883.27  1510.2  885.25  1558.9  888.06  1627.2  897.92
#Mann= 3 , 0 , 0
       0     .05       0  634.52     .04       0   653.3     .05       0
Bank Sta=634.52,653.3
XS Rating Curve= 0 ,0
Exp/Cntr=0.3,0.1

Type RM Length L Ch R = 1 ,40933.4 ,671.4,668.6,664.9
XS GIS Cut Line= 4
     1556790.607      252171.832     1556426.024       252114.54
     1556194.253      251999.957     1555501.545      251929.645
#Sta/Elev= 30
       0  902.33    29.1  897.92      68  889.68    97.1  884.41   116.5  881.83
   174.8  876.07   223.4  869.14   233.1  867.38   262.2  858.76   271.9  856.97
   281.6  856.38   330.2  857.22   378.6  854.66   388.2  852.85   397.8  849.47
   436.1  833.04   444.1  830.22   455.2  828.28   459.1  828.47   522.3  830.86
   560.6  833.39   608.4  834.98     618  836.24   676.6  854.42   774.7  882.15
   813.9  892.83   872.8  907.32  1049.3  946.88  1147.4  969.99  1323.9 1006.19
#Mann= 3 , 0 , 0
       0    .055       0   444.1    .045       0   459.1     .05       0
Bank Sta=444.1,459.1
XS Rating Curve= 0 ,0
Exp/Cntr=0.3,0.1

Type RM Length L Ch R = 1 ,40264.7 ,784.5,795,814.7
XS GIS Cut Line= 4
     1556902.684      251665.833     1556496.434      251530.416
      1556381.85      251492.222     1555434.496      251422.421
#Sta/Elev= 30
       0   870.9   116.8  870.63     146  867.48   165.4  862.96   194.6  848.99
   204.4  845.14   214.1  843.43   350.4   834.4   465.4  828.28   474.7  828.24
   486.1  829.49   493.3  831.42   558.8  862.45   637.1  890.88   695.9  908.06
   754.7  917.42   803.6  923.42   842.8  926.77   911.4  929.02  1019.1  929.38
  1058.2   932.5  1097.4  929.28  1146.4  928.76  1214.9  929.89  1303.1  933.19
  1371.6  928.41  1381.4  929.43  1410.8  944.66  1440.2  954.88  1498.9   969.5
#Mann= 3 , 0 , 0
       0     .05       0   465.4    .045       0   486.1     .08       0
Bank Sta=465.4,486.1
XS Rating Curve= 0 ,0
Exp/Cntr=0.3,0.1

Type RM Length L Ch R = 1 ,39469.8 ,790.7,778.9,765.2
XS GIS Cut Line= 4
     1557327.585      251298.773     1556963.002      251098.252
     1556801.543      250999.294      1556249.46      250811.794
#Sta/Elev= 30
       0  872.73    67.7  862.89    77.4     862    87.1  861.87   106.4  863.13
   125.8  863.05   135.5  861.05   145.2  857.52   164.5  847.92   174.2  843.88
   193.5  838.58   212.9  835.51   270.9  832.49   319.3  834.34     358  833.33
   425.6  829.18   456.4  822.99   463.4  822.36   471.4  822.49   501.3  824.35
   624.9  828.83   634.6  830.14   644.3  833.06   663.8  840.59   673.5  843.68
   702.6     851   819.2  876.15   906.7  891.31    1033  921.53  1188.5  957.14
#Mann= 3 , 0 , 0
       0     .05       0   456.4    .045       0   471.4     .05       0
Bank Sta=456.4,471.4
XS Rating Curve= 0 ,0
Exp/Cntr=0.3,0.1

Type RM Length L Ch R = 1 ,38690.9 ,741.2,738.9,734.1
XS GIS Cut Line= 4
     1557529.854      250592.482     1557161.312      250467.839
     1557039.784      250466.103     1556231.243       250526.51
#Sta/Elev= 30
       0  906.44    38.9  902.23   165.4  885.04   223.7  880.03   233.4  878.61
   262.6  871.78   291.8  867.19   311.2  862.66     321  859.53   330.7  855.51
   359.9   839.9   369.6  836.55     389  832.96   417.1  824.52   428.3  821.73
   435.8  820.74  448.27821.6314   473.2  824.65   501.2   826.7   559.4  826.78
     618  828.72   657.1  832.36   676.7  834.88   696.2  838.37   725.5  845.15
   774.3  858.38   950.2   888.4  1018.6  899.04  1174.8  932.25  1321.4  958.24
#Mann= 3 , 0 , 0
       0     .06       0   428.3    .045       0  448.27     .05       0
Bank Sta=428.3,448.27
XS Rating Curve= 0 ,0
Exp/Cntr=0.3,0.1

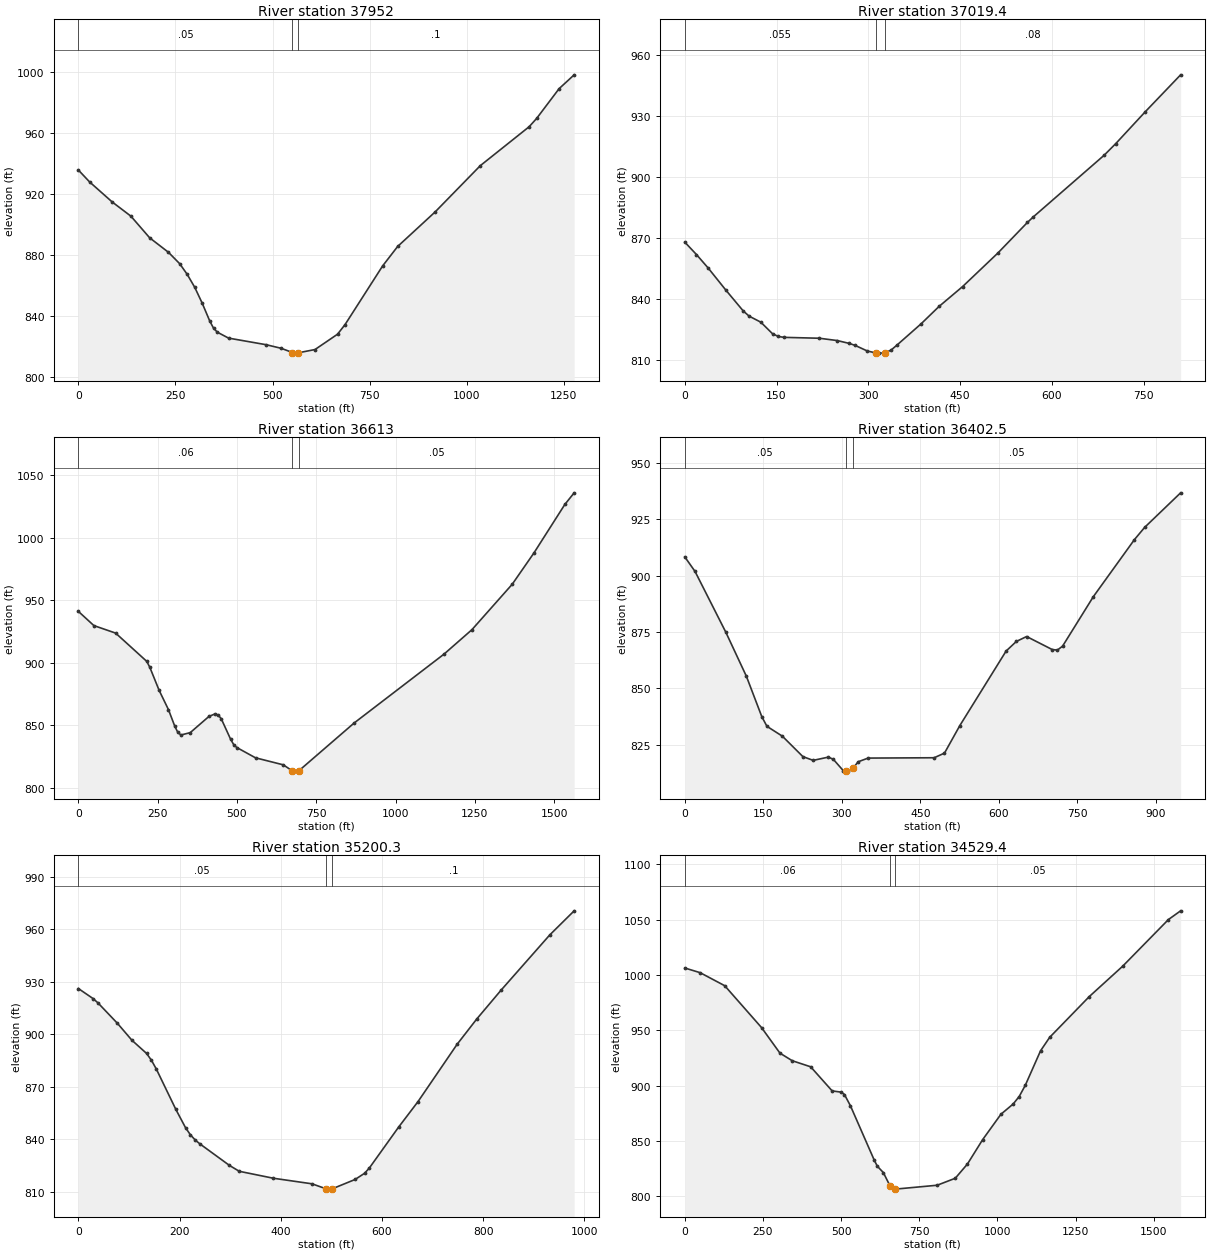
Type RM Length L Ch R = 1 ,37952   ,734.4,932.6,909.1
XS GIS Cut Line= 4
      1557624.46       249881.73     1557229.495      249847.008
     1556903.974      249894.751     1556352.759      249899.091
#Sta/Elev= 30
       0  936.04      29  928.21      87  915.11   135.4  905.75   183.7  891.56
   232.1  882.06   261.1  874.56   280.4  867.58   299.8  859.08   319.1  848.63
   338.5  836.95   348.1  832.35   357.8  829.71   386.8  825.81   483.6  821.48
   522.3  819.13   551.3  816.36     561  815.96   564.7  816.09   609.4  818.31
   667.4  828.36   686.8  834.68   783.5  873.12   822.2  885.89   918.9  908.58
    1035  938.87  1160.7  964.38    1180  969.81    1238  989.38  1276.7  998.43
#Mann= 3 , 0 , 0
       0     .05       0   551.3    .045       0   564.7      .1       0
Bank Sta=551.3,564.7
XS Rating Curve= 0 ,0
Exp/Cntr=0.3,0.1

Type RM Length L Ch R = 1 ,37019.4 ,407.4,406.4,384.1
XS GIS Cut Line= 4
     1557445.966      249567.436     1557257.164      249454.589
     1557090.063      249352.592     1556701.609      249280.978
#Sta/Elev= 30
       0  867.87    19.1  861.76    38.2  855.15    66.9  844.37    95.6  834.02
   105.2  831.48   124.3  828.52   143.4  822.84     153  821.48   162.6  821.05
     220  820.62   249.3  819.48   268.9  818.08   278.7  817.08   298.3  814.36
     312  813.41   317.8   813.3     327  813.37   337.4  814.82   347.2  817.33
   386.4  827.72   415.7  836.25   454.3  846.04   512.1  862.57   560.2  877.56
   569.9   880.3   685.5  910.55   704.8  916.36   752.9  931.98   810.7  950.13
#Mann= 3 , 0 , 0
       0    .055       0     312    .045       0     327     .08       0
Bank Sta=312,327
XS Rating Curve= 0 ,0
Exp/Cntr=0.3,0.1

Type RM Length L Ch R = 1 ,36613   ,208.2,210.5,212.1
XS GIS Cut Line= 4
     1557970.826      249224.427     1557390.965      249127.204
     1557217.354      249109.843     1556418.743      249168.871
#Sta/Elev= 30
       0  941.01      49  929.63   117.6  923.62   215.6  901.06   225.4  896.28
   254.8  877.83   284.2  862.42   303.8  849.37   313.6  844.29   323.4  842.18
   352.8  844.06   411.6  856.97   431.2  859.09     441  858.11   450.8  855.04
   480.2  838.74     490  834.42   499.8  832.14   558.6  823.94   646.1  818.34
   675.2  813.42   684.9   813.3   694.6  813.44   869.8  851.82  1153.1  906.86
    1241  926.37  1367.9  962.65  1436.3  987.65  1533.9 1026.48  1563.2 1035.74
#Mann= 3 , 0 , 0
       0     .06       0   675.2    .045       0   694.6     .05       0
Bank Sta=675.2,694.6
XS Rating Curve= 0 ,0
Exp/Cntr=0.3,0.1

Type RM Length L Ch R = 1 ,36402.5 ,1186.8,1202.2,1192.9
XS GIS Cut Line= 4
     1557709.095      249001.898     1557448.679      248953.721
     1557327.585      248930.283     1556768.883      248909.884
#Sta/Elev= 30
       0   908.4    19.6  901.93    78.5   874.9   117.7  855.39   147.1  837.48
   156.9  833.19   186.4  828.81   225.6  819.74   245.2  818.08   274.3  819.52
   283.8  818.53   302.8   813.5   307.1  813.41   312.3   813.3   322.1  814.83
   331.2  817.45   350.2  819.09   476.4  819.24   496.1   821.3   525.5  833.55
   613.8   866.6   633.4  870.87     653  873.05     702  867.26   711.8  867.04
   721.7  868.78   780.5  890.76     859  916.09   878.6  921.53   947.2  936.84
#Mann= 3 , 0 , 0
       0     .05       0   307.1    .045       0   322.1     .05       0
Bank Sta=307.1,322.1
XS Rating Curve= 0 ,0
Exp/Cntr=0.3,0.1

Type RM Length L Ch R = 1 ,35200.3 ,661.6,670.9,671.1
XS GIS Cut Line= 4
     1558078.019      248214.485     1557654.842      248188.443
     1557496.422      248214.485     1557105.797      248275.249
#Sta/Elev= 30
       0   926.2    28.9  920.48    38.5  918.06    77.1  906.33     106  896.56
   134.9  889.04   144.5  885.12   154.2  880.08   192.7  857.03     212  846.48
   221.6  842.46   231.3  839.42   240.9  837.16   298.7  824.97     318  821.62
   385.4  817.65   461.8  814.46  489.14811.6399   499.5  811.42  502.24811.6585
   546.8  816.93   565.6  820.47   575.1  823.51   632.7  846.82   671.3  861.52
   748.4  894.24     787  908.64   835.2  925.19   931.6  956.85   979.8  970.64
#Mann= 3 , 0 , 0
       0     .05       0  489.14    .045       0  502.24      .1       0
Bank Sta=489.14,502.24
XS Rating Curve= 0 ,0
Exp/Cntr=0.3,0.1

Type RM Length L Ch R = 1 ,34529.4 ,475,477.4,478
XS GIS Cut Line= 4
     1558305.568      247581.232     1557795.151      247596.857
     1557476.902      247663.663     1556791.139      247967.482
#Sta/Elev= 30
       0 1006.23    49.1    1002   127.7  990.23   245.5  952.41   304.4  929.33
   343.7  922.49   402.6  917.01   471.4  895.21   500.8  894.12   510.7  891.95
   529.8  881.81   606.3  832.49   615.9  827.21     635  821.51   656.1  809.62
   673.2  806.55   807.2  810.06   865.1  816.36     904  829.21   952.7  851.25
  1011.2  874.18  1050.1  883.37  1069.6  890.19  1089.1  900.33  1137.8  931.41
    1167  943.59  1293.7  980.41  1400.8 1007.91  1546.9 1049.98  1585.9 1057.85
#Mann= 3 , 0 , 0
       0     .06       0   656.1    .045       0   673.2     .05       0
Bank Sta=656.1,673.2
XS Rating Curve= 0 ,0
Exp/Cntr=0.3,0.1

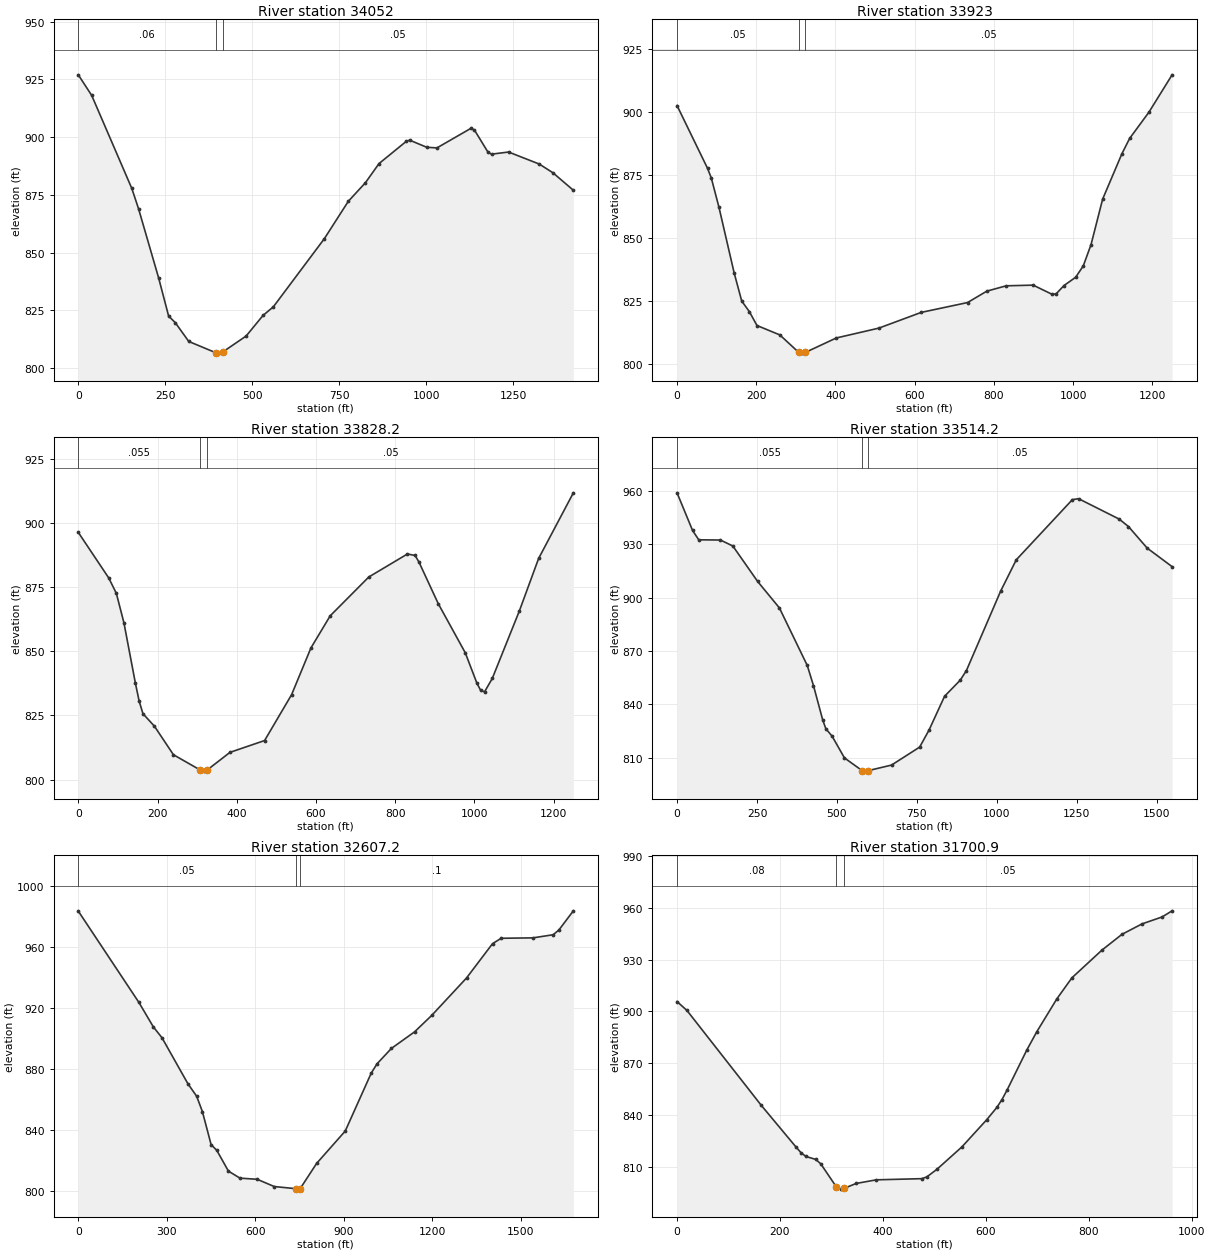
Type RM Length L Ch R = 1 ,34052   ,122.8,129,135
XS GIS Cut Line= 4
     1557765.637      247298.246     1557470.498      247256.579
     1557248.276      247277.413     1556397.582      247576.024
#Sta/Elev= 30
       0  926.95    38.5  918.05   153.8  877.79   173.1  869.03   230.8  839.11
   259.6  822.56   278.8   819.7   317.5  811.57   395.1   806.7   404.8  806.52
   414.5  806.95   482.4  813.92   531.1  822.86   560.5  826.54   707.5  856.12
   776.1  872.23   825.1  880.24   864.3  888.55   942.6  898.16   952.4  898.68
  1001.4   895.6  1030.8  895.33  1128.8  903.83  1138.6  903.04  1177.8   893.4
  1187.6  892.62  1236.6  893.54  1324.8  888.34    1364  884.58  1422.8     877
#Mann= 3 , 0 , 0
       0     .06       0   395.1     .04       0   414.5     .05       0
Bank Sta=395.1,414.5
XS Rating Curve= 0 ,0
Exp/Cntr=0.3,0.1

Type RM Length L Ch R = 1 ,33923   ,95.6,94.8,94.2
XS GIS Cut Line= 4
     1557685.236      247229.635     1557429.159       247147.17
     1557307.632      247125.468     1556450.427       247147.17
#Sta/Elev= 30
       0  902.44    76.9   877.6    86.5  873.74   105.7  862.24   144.1   836.2
   163.3  824.99   182.6  820.79   201.8  815.29   259.4  811.58     307  804.68
   316.5  804.35   323.6   804.6   402.2  810.36   509.4  814.25   616.6  820.49
   733.5  824.39   782.2  828.91     831  831.02   899.2  831.29   947.9  827.58
   957.6  827.91   977.1  831.14  1006.4  834.39  1025.8  838.94  1045.3  847.34
  1074.6  865.37  1123.3  883.37  1142.8  889.43  1191.5  899.82    1250  914.62
#Mann= 3 , 0 , 0
       0     .05       0     307    .045       0   323.6     .05       0
Bank Sta=307,323.6
XS Rating Curve= 0 ,0
Exp/Cntr=0.3,0.1

Type RM Length L Ch R = 1 ,33828.2 ,313.2,314,314.2
XS GIS Cut Line= 4
     1557715.618      247140.659     1557459.541      247058.194
     1557338.014      247036.493     1556480.809      247058.194
#Sta/Elev= 30
       0  896.39    76.9  878.61    96.1   872.6   115.3  861.07   144.1  837.63
   153.7  830.57   163.3  825.66   192.2   820.8   240.2  809.67     307  803.78
   316.5  803.27     326  803.78     383  810.59   470.4   815.2   538.6   833.1
   587.4  851.32   636.1  863.86   733.5  878.99     831  887.96   850.4  887.39
   860.2  884.81   908.9  868.58   977.1  849.43  1006.4   837.6  1016.1  834.74
  1025.8   834.2  1045.3  839.42  1113.5  865.68  1162.3  886.22    1250  911.82
#Mann= 3 , 0 , 0
       0    .055       0     307    .045       0     326     .05       0
Bank Sta=307,326
XS Rating Curve= 0 ,0
Exp/Cntr=0.3,0.1

Type RM Length L Ch R = 1 ,33514.2 ,903.2,907,907.2
XS GIS Cut Line= 4
     1558171.128      246949.808     1557655.503      246814.392
     1557500.774      246786.927     1556643.569      246808.628
#Sta/Elev= 30
       0  958.75    48.5  937.64    67.8  932.38   135.7  932.26   174.5  928.89
     252     909   319.9  894.18   407.1  861.86   426.5  850.57   455.6  831.15
   465.3  826.32   484.6  822.21   523.4  809.96   578.2   802.9   582.2  802.55
  596.27802.7682   670.6  805.95   758.5  816.04   787.7  825.56   836.4  844.58
   885.1  853.55   904.6  858.97  1011.8  903.62  1060.5  921.16  1235.9  954.93
  1255.4  955.45  1382.1  944.03  1411.3  939.83  1469.8  927.72  1547.7  917.32
#Mann= 3 , 0 , 0
       0    .055       0   578.2     .04       0  596.27     .05       0
Bank Sta=578.2,596.27
XS Rating Curve= 0 ,0
Exp/Cntr=0.3,0.1

Type RM Length L Ch R = 1 ,32607.2 ,879.1,906.3,918.7
XS GIS Cut Line= 4
     1558475.155      246224.467     1557891.387      246059.537
     1557659.182      246000.943     1556827.559      245980.313
#Sta/Elev= 30
       0  983.56   205.5  923.75   254.4  907.75   283.7  900.63   371.8  870.45
   401.2  862.35   420.7  852.27   450.1  830.73   469.6  826.88   508.8  813.35
   547.9  808.74   606.6  807.97   664.1  803.24   736.4801.8478   740.7  801.54
  752.13801.8986   807.8  818.38   904.8  839.56   992.9  877.49  1012.5  883.57
  1061.4  893.68  1139.7  904.49  1198.4  915.36  1315.9  939.78    1404  962.23
  1433.3  965.77    1541  966.04  1609.5  968.08    1629  971.21    1678  983.74
#Mann= 3 , 0 , 0
       0     .05       0   736.4    .045       0  752.13      .1       0
Bank Sta=736.4,752.13
XS Rating Curve= 0 ,0
Exp/Cntr=0.3,0.1

Type RM Length L Ch R = 1 ,31700.9 ,619.7,602.6,585.3
XS GIS Cut Line= 4
     1558508.575      245599.901     1558268.991      245438.443
     1558138.783      245318.651      1557693.47      245099.901
#Sta/Elev= 30
       0  905.72    19.3  900.54   163.7  845.51   231.1  821.37   240.8  818.07
   250.4  815.86   269.6  814.15   279.3  811.58   309.1  798.41   318.4  796.92
   324.1  797.29   347.9   800.2   387.2  802.31   475.6  802.99   485.3     804
   504.8  808.37   553.4  821.37     602  837.25   621.5  844.33   631.2  848.77
     641   854.2   679.9  877.75   699.3  888.33   738.2  907.35   767.4  919.51
   825.8  935.59   864.7  944.73   903.6  950.77   942.5  954.78     962  958.34
#Mann= 3 , 0 , 0
       0     .08       0   309.1    .045       0   324.1     .05       0
Bank Sta=309.1,324.1
XS Rating Curve= 0 ,0
Exp/Cntr=0.3,0.1

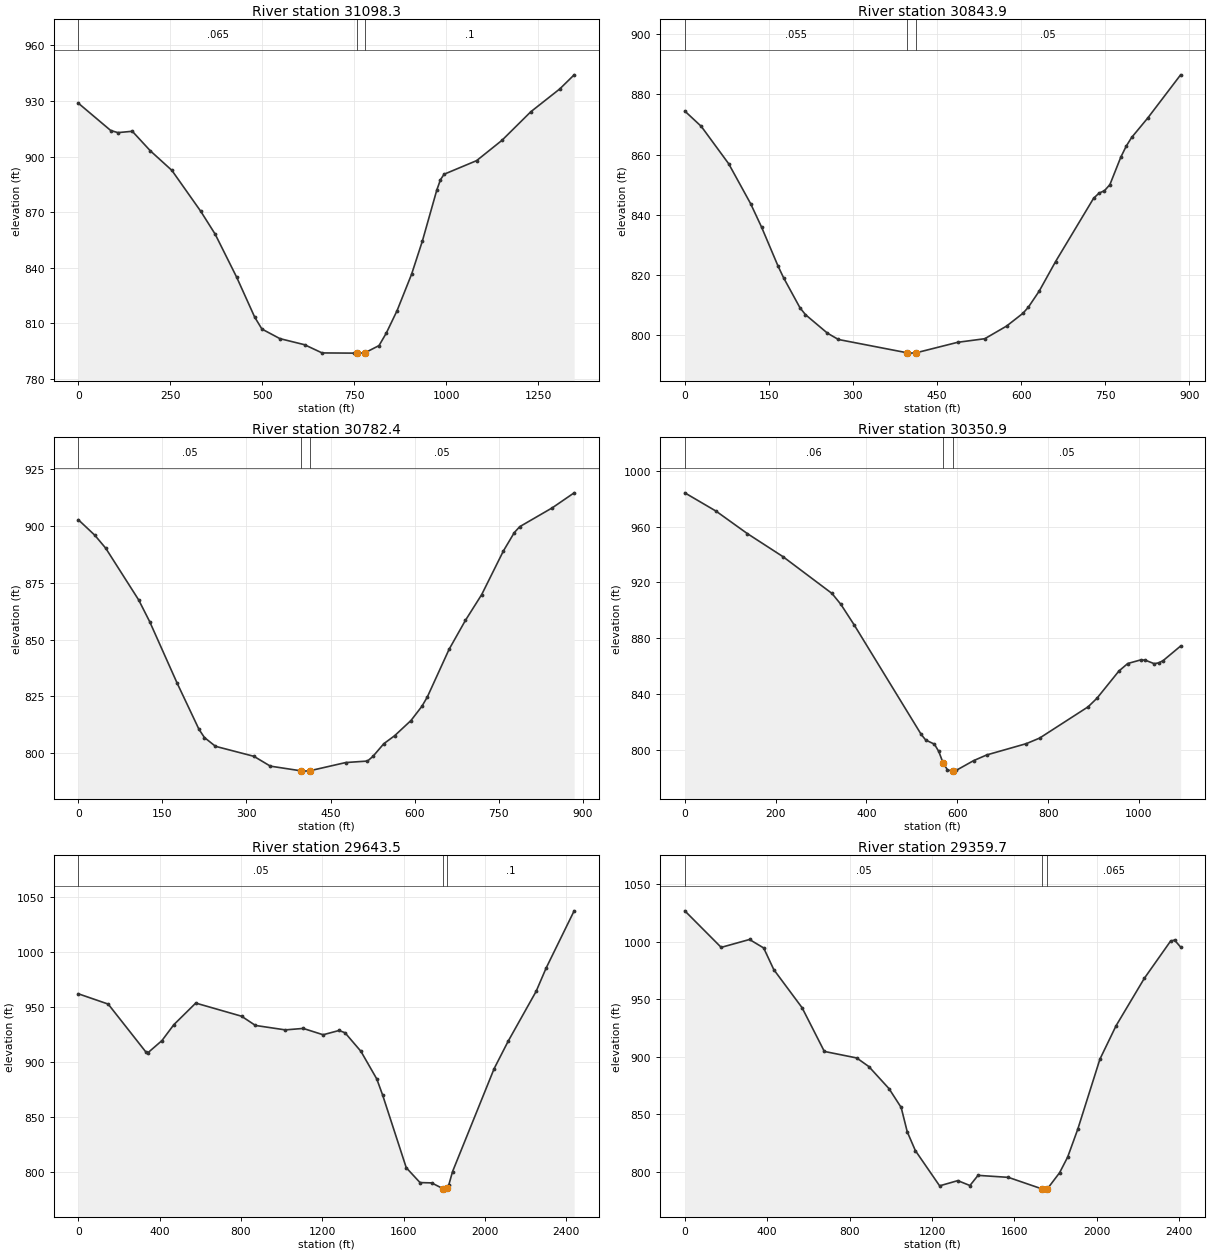
Type RM Length L Ch R = 1 ,31098.3 ,251.2,254.4,257.2
XS GIS Cut Line= 4
      1559123.17      245065.572      1558591.92      244895.434
     1558411.364      244881.545     1557803.725      244839.878
#Sta/Elev= 30
       0   928.8    88.1  914.03   107.6   912.9   146.8  913.62   195.7  903.08
   254.4  892.49   332.7  870.44   371.9   858.1   430.6  834.76   479.5  813.24
   499.1  806.82     548  801.64     615  798.35   662.7  793.92   748.7  793.81
   758.6  793.83   778.3   793.9   817.5  797.89   837.2  804.61   866.6  816.78
   905.9  836.36   935.4  854.37   974.7  881.98   984.5  887.45   994.3  890.41
  1082.8  897.77  1151.5   908.7  1230.1  924.16  1308.7  936.46    1348  944.11
#Mann= 3 , 0 , 0
       0    .065       0   758.6    .045       0   778.3      .1       0
Bank Sta=758.6,778.3
XS Rating Curve= 0 ,0
Exp/Cntr=0.3,0.1

Type RM Length L Ch R = 1 ,30843.9 ,61.4,61.5,61.4
XS GIS Cut Line= 4
     1558928.725      244735.711     1558557.198       244718.35
     1558491.225      244711.406     1558050.253      244641.961
#Sta/Elev= 30
       0  874.48    29.4  869.38    78.3  856.94   117.4  843.67     137  835.84
   166.4  822.87   176.2  819.01   205.5     809   215.3  806.71   254.5  800.55
   274.1  798.44   397.1     794   400.4   793.9   412.1  793.98   486.8   797.5
   535.3   798.7   574.1   802.9   603.2  807.14     613  809.19   632.4  814.56
   661.5  824.35   729.4  845.44   739.1  847.16   748.8  847.97   758.5  849.99
   777.9   859.1   787.6  862.79   797.3  865.69   826.4  872.25   884.7  886.54
#Mann= 3 , 0 , 0
       0    .055       0   397.1     .04       0   412.1     .05       0
Bank Sta=397.1,412.1
XS Rating Curve= 0 ,0
Exp/Cntr=0.3,0.1

Type RM Length L Ch R = 1 ,30782.4 ,428.9,431.5,434
XS GIS Cut Line= 4
     1558939.138      244675.318      1558567.61      244657.957
     1558501.638      244651.013     1558060.666      244581.568
#Sta/Elev= 30
       0   902.6    29.4   895.8    48.9  890.09   107.7  867.37   127.2   857.9
   176.2  830.89   215.3  810.54   225.1  806.93   244.7   803.1   313.2  798.71
   342.6  794.39   397.5  792.32   400.4   792.2   412.5  792.33   477.1  795.97
   515.9  796.62   525.6  798.65     545  804.23   564.4  807.76   593.5  814.42
     613  820.66   622.7  824.76   661.5  845.68   690.6  858.38   719.7  869.73
   758.5  888.92   777.9  896.96   787.6  899.56   845.9  907.87   884.7  914.42
#Mann= 3 , 0 , 0
       0     .05       0   397.5     .04       0   412.5     .05       0
Bank Sta=397.5,412.5
XS Rating Curve= 0 ,0
Exp/Cntr=0.3,0.1

Type RM Length L Ch R = 1 ,30350.9 ,706.3,707.3,707.6
XS GIS Cut Line= 4
     1559242.489      244462.952     1558721.656      244362.258
     1558609.277      244338.513     1558168.305      244269.068
#Sta/Elev= 30
       0  984.16    68.8  971.05   137.5  955.01   216.1  938.46   324.2  912.06
   343.8   904.2   373.3  889.38   520.6  811.09   530.5  807.09   549.6  804.16
   559.2  798.91   568.8  790.62   578.3  785.81   587.9  784.84     590  784.96
   597.5  785.37   635.8  792.34   664.8  796.44   752.1  804.54   781.2   808.5
     888   830.9   907.4  837.01   955.9  856.56   975.3  861.92  1004.4  864.55
  1014.1  864.27  1033.5   861.8  1043.2  862.37  1052.9  863.92  1091.7  874.44
#Mann= 3 , 0 , 0
       0     .06       0   568.8     .04       0     590     .05       0
Bank Sta=568.8,590
XS Rating Curve= 0 ,0
Exp/Cntr=0.3,0.1

Type RM Length L Ch R = 1 ,29643.5 ,289.6,283.8,277.6
XS GIS Cut Line= 5
     1560246.175      244743.073     1559120.191      243831.778
     1558888.536      243711.823     1558725.341      243670.157
     1558164.836       243655.85
#Sta/Elev= 30
       0  962.31   146.8  952.96   332.8  909.29   342.6  908.79   411.1  919.77
   469.8  934.26   577.5  953.87   802.6  941.94   871.1  933.54  1017.9  929.51
    1106  930.84  1203.9  925.09  1282.2  928.96  1311.5  926.93  1389.8  910.02
  1467.9  884.88  1496.9   870.1  1612.8  804.25  1680.4  790.76  1737.5  790.48
  1793.6  785.23    1803  784.81  1814.4  785.82  1821.7  788.45  1840.4  800.75
  2045.1  894.35  2113.9  919.22  2251.6  964.57  2300.8  985.77  2438.5  1037.7
#Mann= 3 , 0 , 0
       0     .05       0  1793.6    .045       0  1814.4      .1       0
Bank Sta=1793.6,1814.4
XS Rating Curve= 0 ,0
Exp/Cntr=0.3,0.1

Type RM Length L Ch R = 1 ,29359.7 ,1120.2,1110.9,1099.3
XS GIS Cut Line= 4
     1560565.619      243447.935     1558887.007       243427.04
     1558746.382       243427.04     1558160.642      243379.778
#Sta/Elev= 30
       0 1026.85   176.7  995.06   314.2 1001.92   382.9  994.55     432  975.72
   569.4  942.57   677.4  904.56   834.5  898.89   893.4  891.41   991.5  872.17
  1050.4  855.81  1079.9  834.65  1119.2  818.33    1237  787.66  1325.3  792.19
  1384.2  787.93  1423.5  796.78  1570.8  795.03    1735  784.93  1753.7   784.8
  1760.4  785.13  1819.4  799.06  1858.5  812.63  1907.5  836.82  2015.2  897.85
  2093.6   926.9  2230.7  968.12    2358 1000.47  2377.6 1001.42    2407   995.3
#Mann= 3 , 0 , 0
       0     .05       0    1735    .045       0  1760.4    .065       0
#XS Ineff= 2 , 0
         1567.05  794.94
Permanent Ineff=
       F       F
Bank Sta=1735,1760.4
XS Rating Curve= 0 ,0
Exp/Cntr=0.3,0.1