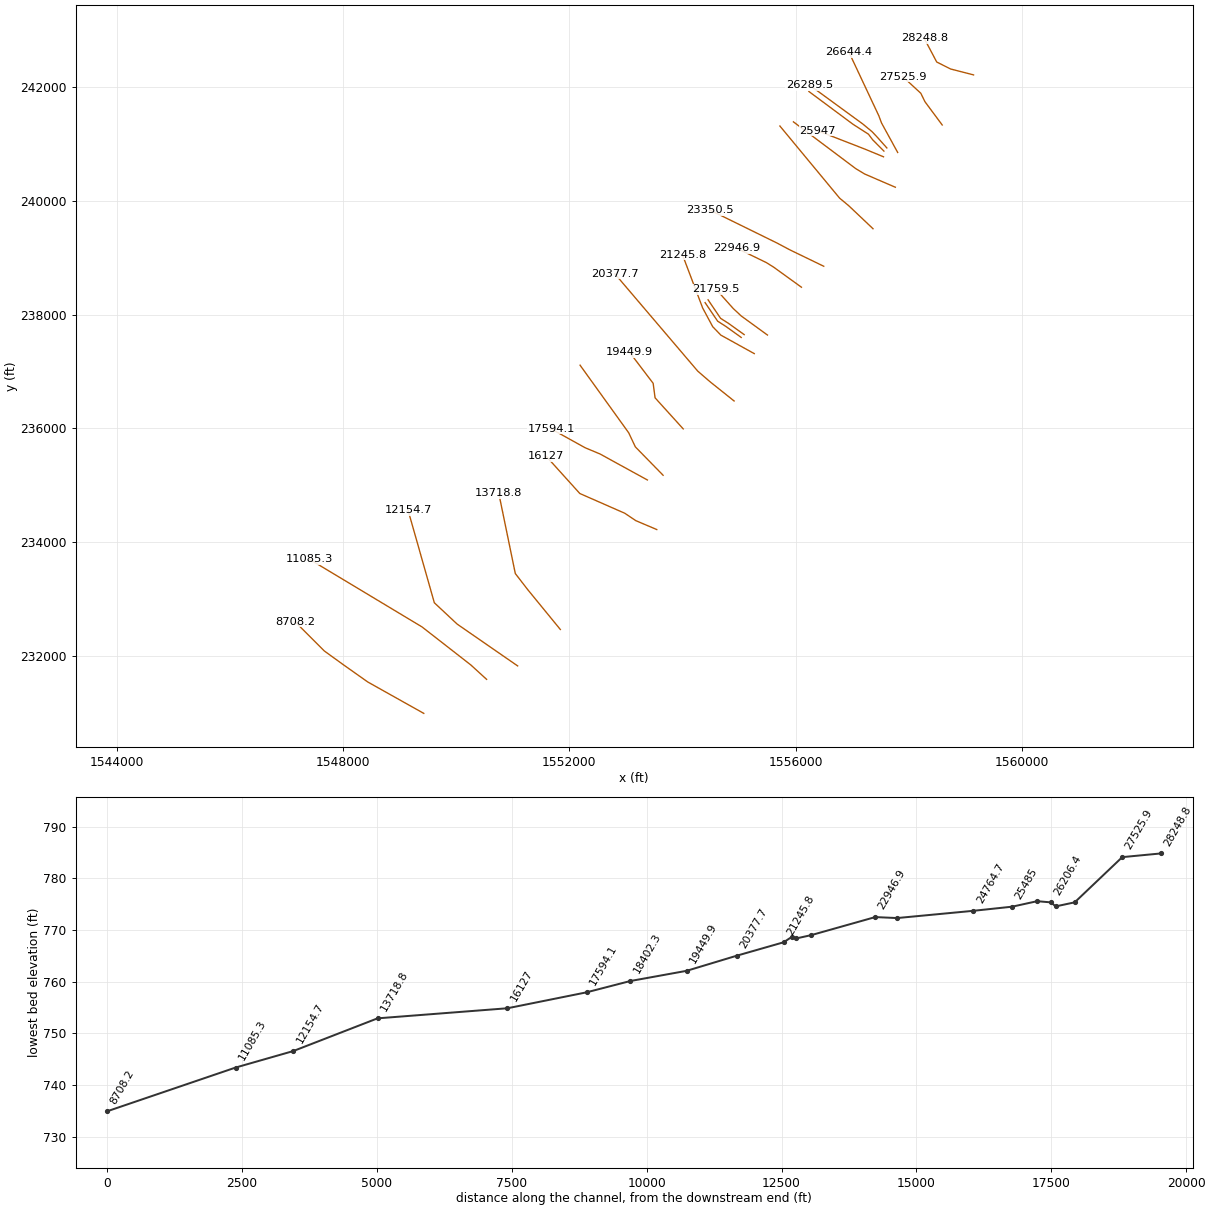
HEC-RAS study SLBCR.prj: SLBCR

--- SLBCR.g01 (geometry) --- (continued)

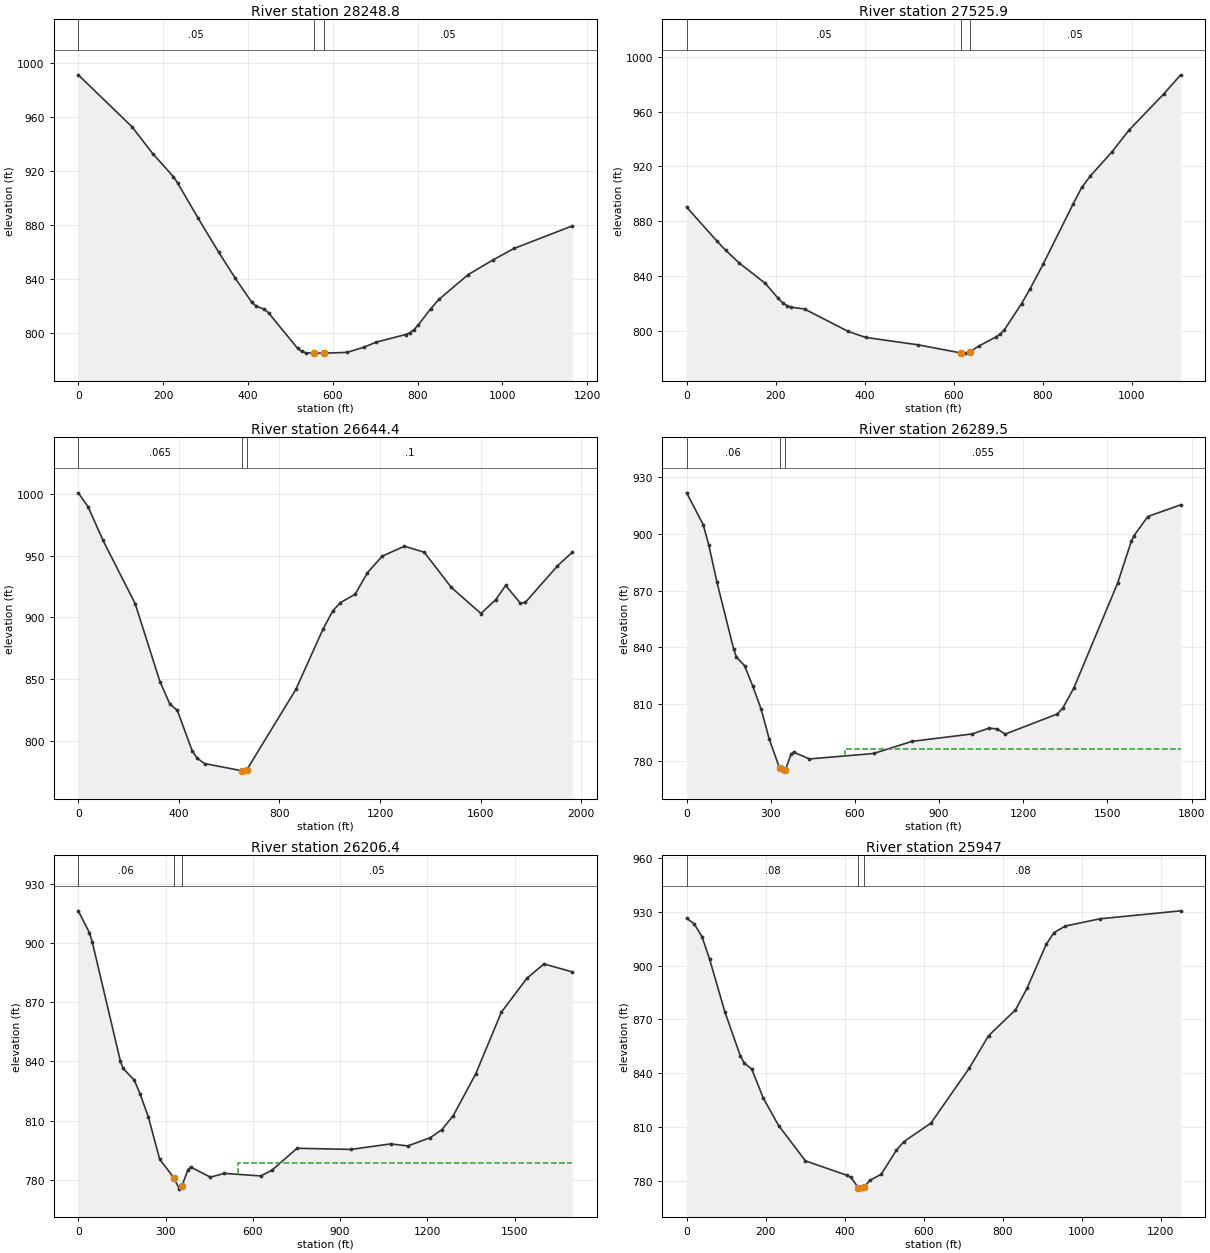
Type RM Length L Ch R = 1 ,28248.8 ,737.9,723,707.8
XS GIS Cut Line= 4
     1559140.953      242218.536     1558734.703      242322.702
     1558489.911      242445.098     1558268.557      242861.765
#Sta/Elev= 30
       0  991.58   126.8  952.96   175.6  933.06   224.3  915.95   234.1  911.36
   282.8  884.99   331.6  859.57   370.6  840.26   409.6  822.42   419.4  819.71
   438.9  817.45   448.7  814.75   517.1   788.4   526.9  786.09   536.7  785.06
   556.2   784.8   579.8   784.8   634.4  785.36   673.5  789.21   702.9  792.98
   771.7  798.59   781.5  799.91   791.4  802.17   801.2  805.53   830.7  817.63
   850.4   824.7   919.2  843.09   978.1  854.08  1027.3  862.54  1164.9  879.33
#Mann= 3 , 0 , 0
       0     .05       0   556.2    .045       0   579.8     .05       0
Bank Sta=556.2,579.8
XS Rating Curve= 0 ,0
Exp/Cntr=0.3,0.1

Type RM Length L Ch R = 1 ,27525.9 ,883.3,881.4,879
XS GIS Cut Line= 4
       1558586.7      241337.749     1558282.012      241746.603
     1558209.095       241895.04     1557888.783      242189.311
#Sta/Elev= 30
       0  890.37    68.6  865.46    88.2  858.85   117.7  849.83   176.5  834.93
   205.9   823.9   215.7  820.72   225.5   818.6   235.3  817.52   264.8   816.2
   362.8  799.92     402  795.53   519.6  790.15   616.9  784.16   626.6  784.08
   636.4  785.05   655.8  789.09   694.6   795.8   704.3  797.81   713.9  801.02
   752.6  820.14   771.9  831.02   800.9  848.79   868.6  892.81   887.9  904.82
   907.3  913.13   955.6  930.62   994.2  946.52  1071.6  972.66  1110.2  986.75
#Mann= 3 , 0 , 0
       0     .05       0   616.9    .045       0   636.4     .05       0
Bank Sta=616.9,636.4
XS Rating Curve= 0 ,0
Exp/Cntr=0.3,0.1

Type RM Length L Ch R = 1 ,26644.4 ,344.5,354.9,365.1
XS GIS Cut Line= 4
     1557800.253      240853.767     1557515.531      241371.128
      1557466.92        241499.6     1556939.142      242617.656
#Sta/Elev= 30
       0 1001.13    39.4  989.73    98.4  962.58   226.4  911.18   324.8  848.02
   364.2  829.76   393.7  824.71   452.7  792.06   472.4  785.87     502   781.5
   649.4  775.69   659.2  775.34   670.3  776.47   865.3  841.66   973.2  890.56
  1012.4  905.46  1041.9  912.01  1100.8  918.84  1149.8  936.26  1208.7  949.78
    1297  957.81  1375.5  952.96  1483.4  924.38  1601.2  903.22  1660.1  914.55
  1699.3  925.95  1758.2  911.55  1777.8  912.26  1905.4  941.86  1964.3  952.94
#Mann= 3 , 0 , 0
       0    .065       0   649.4    .045       0   670.3      .1       0
Bank Sta=649.4,670.3
XS Rating Curve= 0 ,0
Exp/Cntr=0.3,0.1

Type RM Length L Ch R = 1 ,26289.5 ,85.8,83.1,80.6
XS GIS Cut Line= 5
     1557609.281      240933.628     1557425.253      241138.489
     1557345.392      241221.822      1557185.67      241353.767
     1556244.698      242037.795
#Sta/Elev= 30
       0   921.8      59  904.93    78.7  894.29   108.2  874.38   167.2   839.3
     177  835.01   206.5  830.32     236  819.45   265.6  807.31   294.6   791.4
  331.33 776.057   342.7  774.55   352.3  775.33   371.6  783.35   381.2  784.59
   437.9     781   666.4  783.88   803.3   790.3  1018.3  794.23    1077  797.26
  1106.3  796.93  1135.6  794.14  1321.4  804.78  1340.9  807.93    1380  818.43
  1536.4  874.03  1585.3  896.24  1595.1  899.22    1644  909.27  1761.3  915.46
#Mann= 3 , 0 , 0
       0     .06       0  331.33    .045       0   352.3    .055       0
#XS Ineff= 2 , 0
                          564.71          786.27
Permanent Ineff=
       F       F
Bank Sta=331.33,352.3
XS Rating Curve= 0 ,0
Exp/Cntr=0.3,0.1

Type RM Length L Ch R = 1 ,26206.4 ,246.7,259.4,271.7
XS GIS Cut Line= 5
     1557557.198      240878.072     1557359.281      241075.989
     1557282.892      241176.684     1557015.531      241346.822
     1556231.371      241926.762
#Sta/Elev= 30
       0  916.26    38.6  905.14    48.3  900.44   144.8  840.22   154.4  836.44
     193  830.44   212.3  823.64   241.3   811.8   279.9   790.5   328.5  781.12
     348  775.33   356.6  776.99   377.1   785.2   386.8  786.48   454.3  781.39
   502.3   783.3   627.2  782.01   665.6  784.86   752.4  796.02   937.8  795.45
  1074.3  798.24  1132.8  797.19  1210.8  801.44  1249.9  805.43  1288.9  812.47
  1366.9  833.82  1454.7  864.94  1542.5  882.09    1601  889.37  1698.5  885.33
#Mann= 3 , 0 , 0
       0     .06       0   328.5    .045       0   356.6     .05       0
#XS Ineff= 2 , 0
                          547.83          788.46
Permanent Ineff=
       F       F
Bank Sta=328.5,356.6
XS Rating Curve= 0 ,0
Exp/Cntr=0.3,0.1

Type RM Length L Ch R = 1 ,25947   ,465.8,462,458.1
XS GIS Cut Line= 4
     1557550.241      240777.853     1557227.325      240910.665
     1557039.825      240983.582     1556386.179      241236.186
#Sta/Elev= 30
       0  926.34    19.4  923.12    38.8  916.07    58.2  903.45      97  874.01
   135.8  849.81   145.5  845.79   164.9  842.35     194  826.23   232.8  810.97
   300.7   791.3   406.6   783.2   416.2  782.07   434.2  776.46     445  775.56
   449.2  776.71   464.1  780.47   492.9  783.89   531.2  797.27   550.3  802.05
   618.5  812.29   715.8  842.95   764.5  860.96   832.6  875.32   861.8  887.29
   910.4  911.74   929.9   918.3   959.1  921.99  1046.7  926.02  1251.1  930.45
#Mann= 3 , 0 , 0
       0     .08       0   434.2    .045       0   449.2     .08       0
Bank Sta=434.2,449.2
XS Rating Curve= 0 ,0
Exp/Cntr=0.3,0.1

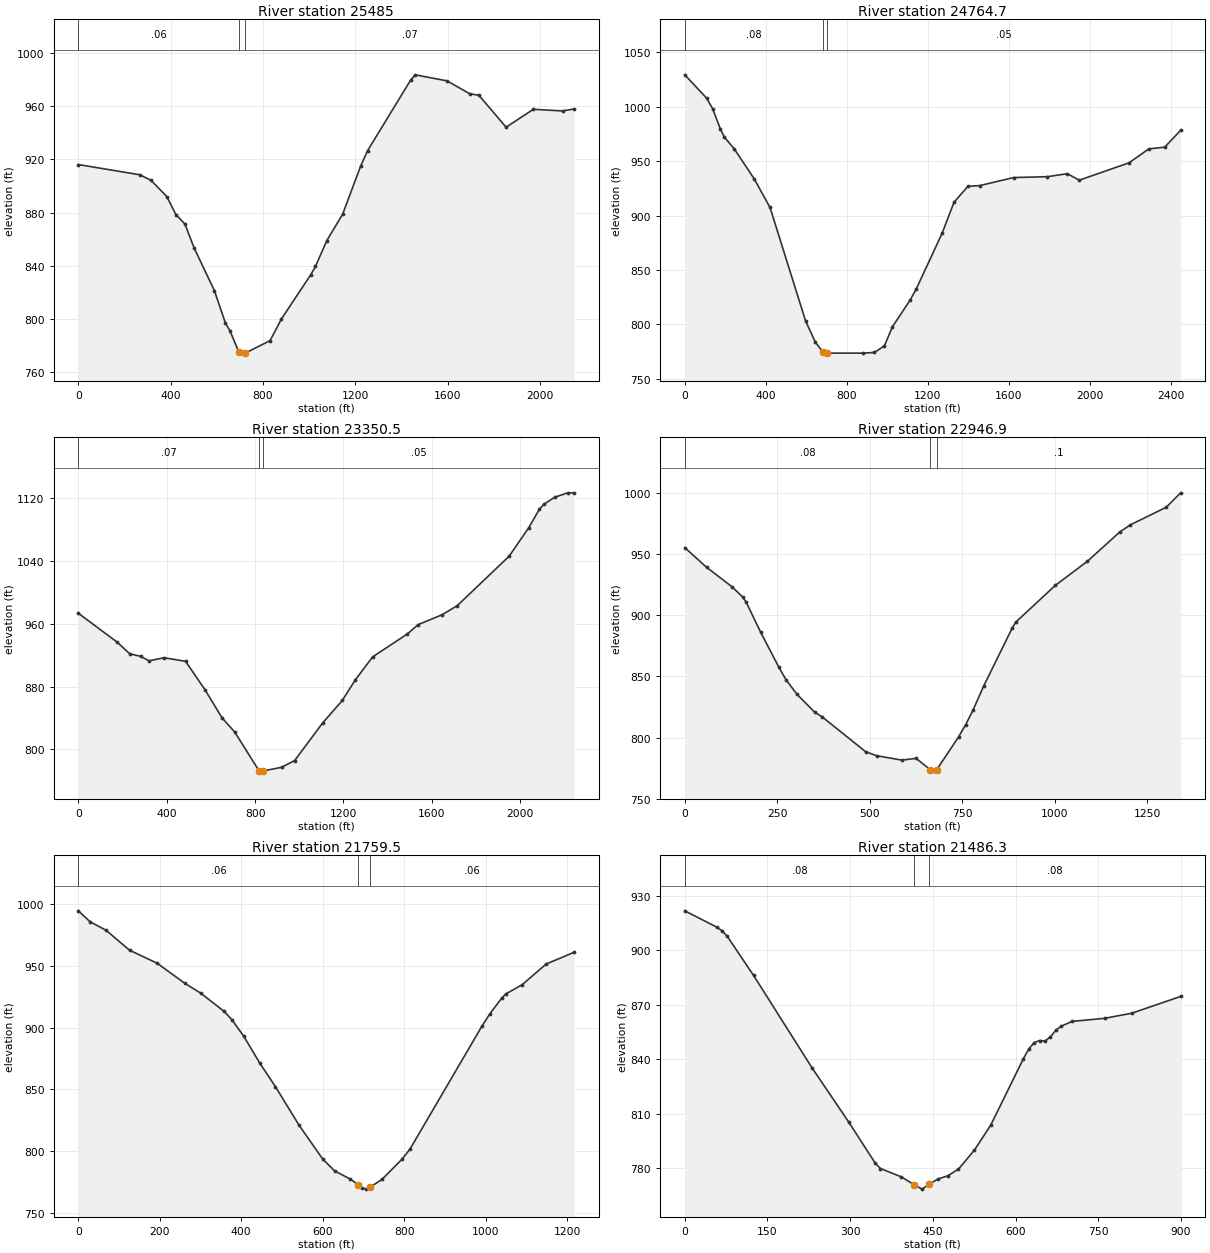
Type RM Length L Ch R = 1 ,25485   ,722.6,720.3,717
XS GIS Cut Line= 4
     1557758.586      240242.656      1557216.92      240475.295
      1557060.67      240569.045     1555957.933      241392.907
#Sta/Elev= 30
       0  916.08   265.3  908.45   314.4  904.33   383.2  892.08   422.5  878.58
   461.8  871.45   501.1  853.69   589.5  821.43   637.5  796.96   656.6  791.41
     695  775.45   714.2   774.5   723.8  774.59   830.7  783.87   879.9  800.14
  1007.7  833.52  1027.4  839.63  1076.5  858.96  1145.4  878.93    1224   915.3
  1253.5  926.62  1440.3  979.64    1460  983.46  1597.6  978.92    1696  969.22
  1735.3  968.15  1853.3  944.13  1971.3  957.56  2099.1  956.34  2148.2  957.88
#Mann= 3 , 0 , 0
       0     .06       0     695    .045       0   723.8     .07       0
Bank Sta=695,723.8
XS Rating Curve= 0 ,0
Exp/Cntr=0.3,0.1

Type RM Length L Ch R = 1 ,24764.7 ,1409,1414.2,1418
XS GIS Cut Line= 4
     1557364.055      239513.055     1556936.972      239915.833
     1556773.777       240051.25     1555719.218      241319.123
#Sta/Elev= 30
       0 1029.14   107.6 1007.74     137  998.19   176.1  979.21   195.7  971.94
   244.6  961.08   342.4  933.73   420.7  907.43   596.7  803.07   644.9   783.7
   681.5  774.78   702.7  773.72   877.6   773.7   936.5  774.31   985.6   780.4
  1024.9  797.78  1113.2  822.57  1142.7  832.51  1270.3  883.62  1329.2  912.13
  1397.9  926.81  1456.8  927.51  1623.7  934.85  1790.6  935.66  1888.7   938.4
  1947.6  932.44    2193  948.34  2291.2  961.17  2369.7  962.74  2448.2  978.24
#Mann= 3 , 0 , 0
       0     .08       0   681.5    .045       0   702.7     .05       0
Bank Sta=681.5,702.7
XS Rating Curve= 0 ,0
Exp/Cntr=0.3,0.1

Type RM Length L Ch R = 1 ,23350.5 ,405.1,403.6,402.3
XS GIS Cut Line= 4
     1556494.264      238852.465     1555890.965      239143.263
     1555669.611      239260.451     1554480.375      239842.048
#Sta/Elev= 30
       0  973.56   174.7  936.93     233  921.82   281.5  918.68   320.3   912.9
   388.2  916.82   485.3  912.29   572.7  876.29   650.3  840.29   708.3  821.94
   817.1  773.05   823.9   772.3   833.5  772.32   920.2  777.22     979   785.8
  1106.5  833.97  1194.8  862.44  1253.6  888.63    1332  917.94    1489  947.13
    1538  959.04  1645.8  971.58  1714.5  983.11  1949.8  1046.3  2038.1 1082.46
  2087.1 1106.35  2106.7 1112.45  2155.8 1121.39  2214.6 1127.04    2244 1127.06
#Mann= 3 , 0 , 0
       0     .07       0   817.1    .045       0   833.5     .05       0
Bank Sta=817.1,833.5
XS Rating Curve= 0 ,0
Exp/Cntr=0.3,0.1

Type RM Length L Ch R = 1 ,22946.9 ,1191.7,1187.4,1182.8
XS GIS Cut Line= 4
      1556099.72      238483.582     1555607.533      238837.749
     1555477.325      238918.478     1554953.887      239171.082
#Sta/Elev= 30
       0   955.5    58.7  939.44   127.1  923.57   156.5  915.12   166.3  910.61
   205.4  886.08   254.3  857.59   273.8  847.28   303.2  835.45   352.1   820.5
   371.6   816.9     489   788.4   518.4  785.14   586.8  781.51   625.5  782.95
   663.8  773.64   673.4  772.49   681.2  773.66   740.4  800.54   759.6  810.58
     779  822.18     808  842.02   885.5  889.73   895.2  894.53  1001.7  924.52
  1088.9  944.33  1176.1  968.25  1205.2  974.21    1302  988.56  1340.8 1000.36
#Mann= 3 , 0 , 0
       0     .08       0   663.8    .045       0   681.2      .1       0
Bank Sta=663.8,681.2
XS Rating Curve= 0 ,0
Exp/Cntr=0.3,0.1

Type RM Length L Ch R = 1 ,21759.5 ,269.7,273.2,276.7
XS GIS Cut Line= 4
     1555499.472      237642.395     1555036.926       237977.34
     1554894.565      238109.285     1554592.482       238446.09
#Sta/Elev= 30
       0  994.61      29  985.72    67.8   978.9   125.8  962.68   193.6  952.12
   261.3   935.9   300.1  927.97   358.1  913.08   377.5  906.19   406.5  892.81
   445.2  871.36     484  852.08     542  820.84   600.2  793.35   629.3   783.8
   668.1  777.09   687.6  772.53   697.2  769.98     707     769   716.7   770.6
   745.8  776.93   794.7  793.19   814.4  801.44   991.4  901.28  1011.1  911.36
  1040.6  924.23  1050.4  927.34  1089.8   934.7  1148.8  951.46  1217.6  961.02
#Mann= 3 , 0 , 0
       0     .06       0   687.6    .045       0   716.7     .06       0
Bank Sta=687.6,716.7
XS Rating Curve= 0 ,0
Exp/Cntr=0.3,0.1

Type RM Length L Ch R = 1 ,21486.3 ,78.2,78.6,79
XS GIS Cut Line= 4
     1555088.014      237650.208     1554814.576       237845.52
     1554671.347      237936.666     1554449.993      238262.187
#Sta/Elev= 30
       0  921.61    57.6  912.69    67.2  910.71    76.8  907.68   124.8  886.02
   230.4  835.34   297.6  805.19   345.5  782.64   354.9  779.71   392.6  775.15
  416.24770.7271   430.4  768.37  443.87771.1736   458.6  773.86   477.5  775.79
   496.4  779.37   525.5  789.92     555  803.64     614  840.07   623.9  845.53
   633.7  849.03   643.6  850.19   653.4  849.92   663.3   852.2   673.1  855.84
   682.9  858.11   702.6  860.72   761.7  862.43   810.9  865.24   899.4  874.47
#Mann= 3 , 0 , 0
       0     .08       0  416.24    .045       0  443.87     .08       0
Bank Sta=416.24,443.87
XS Rating Curve= 0 ,0
Exp/Cntr=0.3,0.1

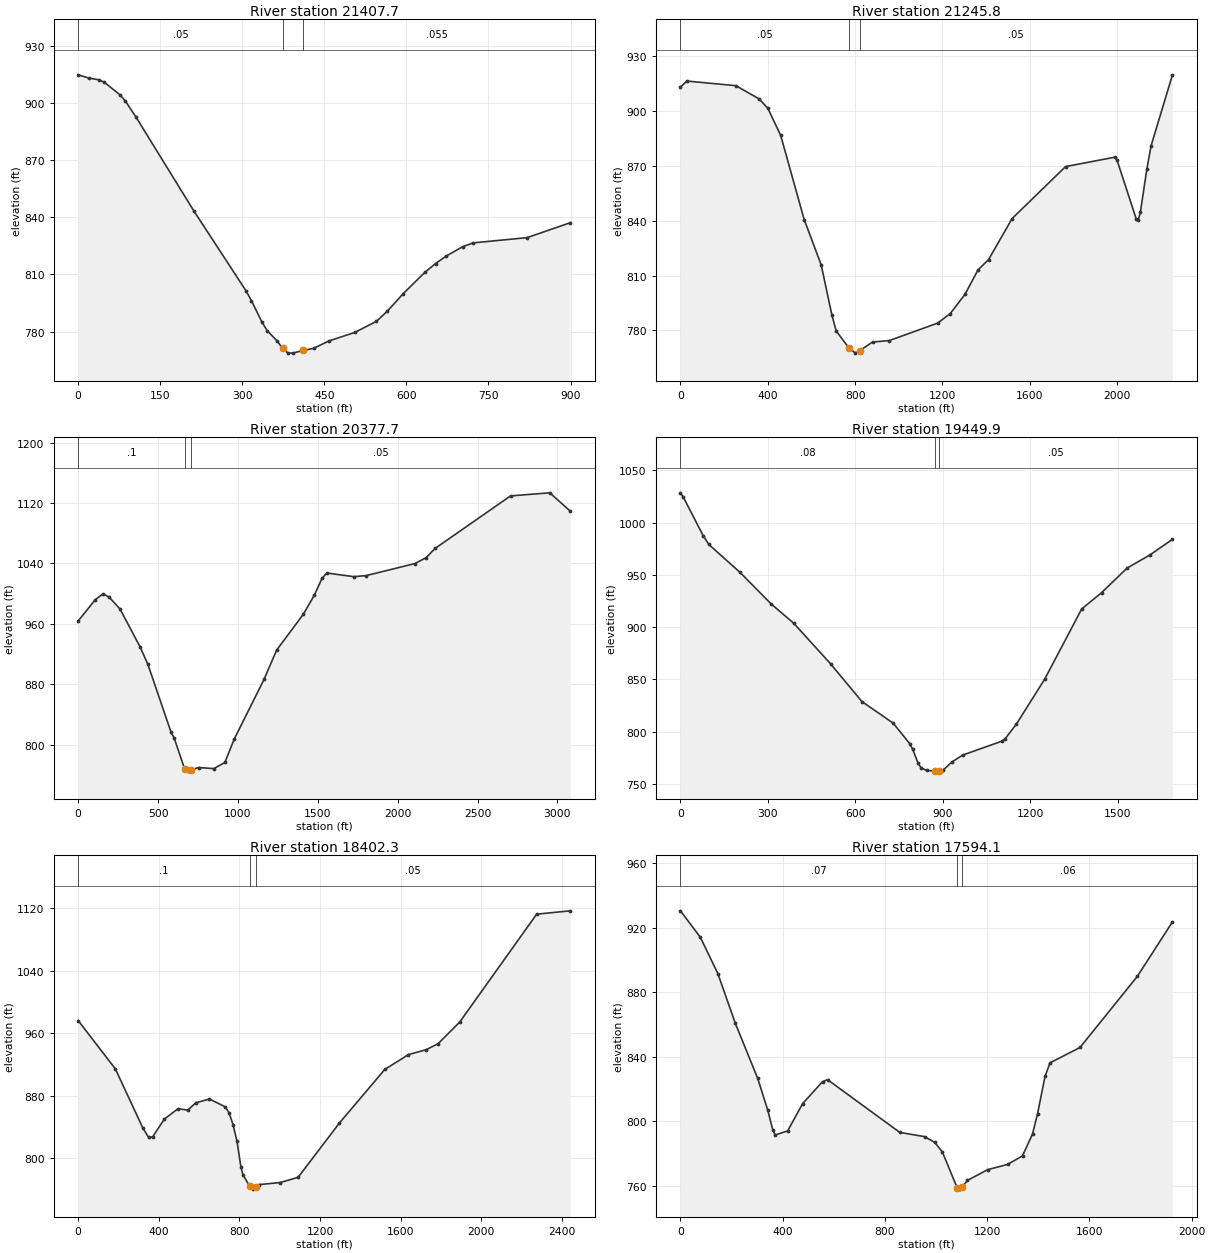
Type RM Length L Ch R = 1 ,21407.7 ,167.2,161.8,156.4
XS GIS Cut Line= 4
      1555035.93      237600.295     1554762.493      237795.607
     1554619.264      237886.753     1554397.909      238212.274
#Sta/Elev= 30
       0  914.84    19.2  913.17    38.4   912.2      48   910.9    76.8  904.27
    86.4  901.03   105.6  892.73   211.2  843.51   307.2  801.29   316.8   796.2
     336     785   345.5  780.55   364.3  774.91   373.8  771.16   383.2   768.8
   392.2  768.71   411.5  770.12   430.4  771.23   458.6  775.13   505.8  779.59
   545.2   785.4   564.8  790.63   594.4  799.99   633.7  811.11   653.4  815.76
   673.1  819.74   702.6  824.55   722.3  826.61   820.7  829.35   899.4  837.17
#Mann= 3 , 0 , 0
       0     .05       0   373.8     .04       0   411.5    .055       0
Bank Sta=373.8,411.5
XS Rating Curve= 0 ,0
Exp/Cntr=0.3,0.1

Type RM Length L Ch R = 1 ,21245.8 ,865.6,868.1,870.2
XS GIS Cut Line= 5
     1555265.965      237316.006     1554675.687      237641.527
     1554532.458      237789.097     1554354.507      238118.958
     1553998.604      239052.118
#Sta/Elev= 30
       0  913.03    29.3  916.41     254  913.87   361.5  906.56   400.5  901.44
   459.2  886.65   566.6  840.67   644.8   815.8   693.7  788.36   713.3  779.72
     772   770.4   801.4  767.61     821  768.94   879.7  773.69   956.6  774.48
  1177.6  784.01  1235.3  789.18  1303.5  799.82  1362.2  813.03  1411.2   818.8
  1518.9  841.22  1763.7  869.63  1988.9  874.76  1998.7  873.41  2086.8  841.19
  2096.6  840.34  2106.4  844.78  2135.8  868.08  2155.4  881.04  2253.3  919.81
#Mann= 3 , 0 , 0
       0     .05       0     772     .04       0     821     .05       0
Bank Sta=772,821
XS Rating Curve= 0 ,0
Exp/Cntr=0.3,0.1

Type RM Length L Ch R = 1 ,20377.7 ,941.7,927.8,911.2
XS GIS Cut Line= 4
     1554910.062      236482.673     1554484.715      236821.215
     1554267.701      237007.847     1552805.027      238717.916
#Sta/Elev= 30
       0  963.76   106.8  991.85   155.3  999.69   194.2  995.33   262.1  979.65
   388.3  929.29   436.8  906.23   581.8  816.42   600.9  808.94   667.7  767.19
   686.7  765.02   705.8   766.5   753.5   769.8   849.5  768.39   918.3  776.49
   977.2  807.46    1164  886.67  1242.6  925.23  1409.6  972.65  1478.4  997.87
  1527.5  1020.5    1557 1027.29  1724.1 1022.49  1802.7 1023.85  2107.3 1039.75
  2176.1  1047.3    2235 1059.91  2706.7 1129.37  2952.4 1133.44  3080.1 1109.31
#Mann= 3 , 0 , 0
       0      .1       0   667.7    .045       0   705.8     .05       0
Bank Sta=667.7,705.8
XS Rating Curve= 0 ,0
Exp/Cntr=0.3,0.1

Type RM Length L Ch R = 1 ,19449.9 ,1043.4,1047.6,1053.4
XS GIS Cut Line= 4
     1554011.179      235991.394     1553513.783      236538.269
     1553479.929      236793.478     1553060.658      237342.957
#Sta/Elev= 30
       0 1028.43     9.7 1024.44    77.8  987.51    97.3  979.03   204.3  952.32
   311.3  922.04   389.1   903.5   515.5  864.63   622.5  828.68   729.5   808.1
   786.9  788.29   796.4  783.13   815.5  769.46     825  765.49   844.1  762.79
   872.7   762.1     873   762.1     888   762.1   901.3  763.07   929.9  770.56
   968.1  777.46  1103.8  790.87  1113.5  792.97  1152.4  807.09  1249.8  850.26
  1376.3  917.28  1444.5  932.86  1532.1  956.42    1610  968.89  1687.8  983.94
#Mann= 3 , 0 , 0
       0     .08       0     873    .045       0     888     .05       0
Bank Sta=873,888
XS Rating Curve= 0 ,0
Exp/Cntr=0.3,0.1

Type RM Length L Ch R = 1 ,18402.3 ,791.6,808.3,824.9
XS GIS Cut Line= 4
     1553655.722       235176.25      1553165.27      235675.381
     1553048.083      235922.777     1552188.708      237112.013
#Sta/Elev= 30
       0  976.27   184.7  914.24   320.7  838.62   349.9  826.32   369.3  827.04
   427.6  849.92   495.7  863.26   544.3  861.36   583.1   870.7   651.2   875.6
   729.1  865.77   748.6  857.94   768.2  842.88   787.8  821.88   807.3  788.66
   817.1  778.67  850.48764.1921     866  760.12  879.93762.4564   895.3  765.84
  1002.9  768.61  1090.9  775.23  1296.3  844.93  1521.3   913.6  1638.7  932.61
  1726.7  938.86  1785.4  946.53    1893  974.37  2274.5 1112.61  2440.8 1116.89
#Mann= 3 , 0 , 0
       0      .1       0  850.48    .045       0  879.93     .05       0
Bank Sta=850.48,879.93
XS Rating Curve= 0 ,0
Exp/Cntr=0.3,0.1

Type RM Length L Ch R = 1 ,17594.1 ,1471.3,1467,1462.5
XS GIS Cut Line= 4
     1553378.366      235092.957     1552539.825       235551.29
     1552276.804      235660.665     1551677.845      235991.394
#Sta/Elev= 30
       0  930.54      78  914.11   146.3  891.63   214.5  860.88   302.3  826.58
   341.3  807.05   360.8  794.89   370.6  791.51   419.3  794.02   477.8  810.93
   555.8  824.59   575.3  825.84   858.1  793.12   955.6  790.48   994.9  786.89
  1024.4  781.06  1083.3  758.43  1093.1  757.94    1103  759.32  1122.6  763.34
  1201.2  769.97  1279.6  773.26  1338.2   778.6  1377.3  792.16  1396.9  804.72
  1426.2  827.82  1445.7  836.29    1563  845.78  1787.8  890.01  1924.7  923.72
#Mann= 3 , 0 , 0
       0     .07       0  1083.3    .045       0    1103     .06       0
Bank Sta=1083.3,1103
XS Rating Curve= 0 ,0
Exp/Cntr=0.3,0.1

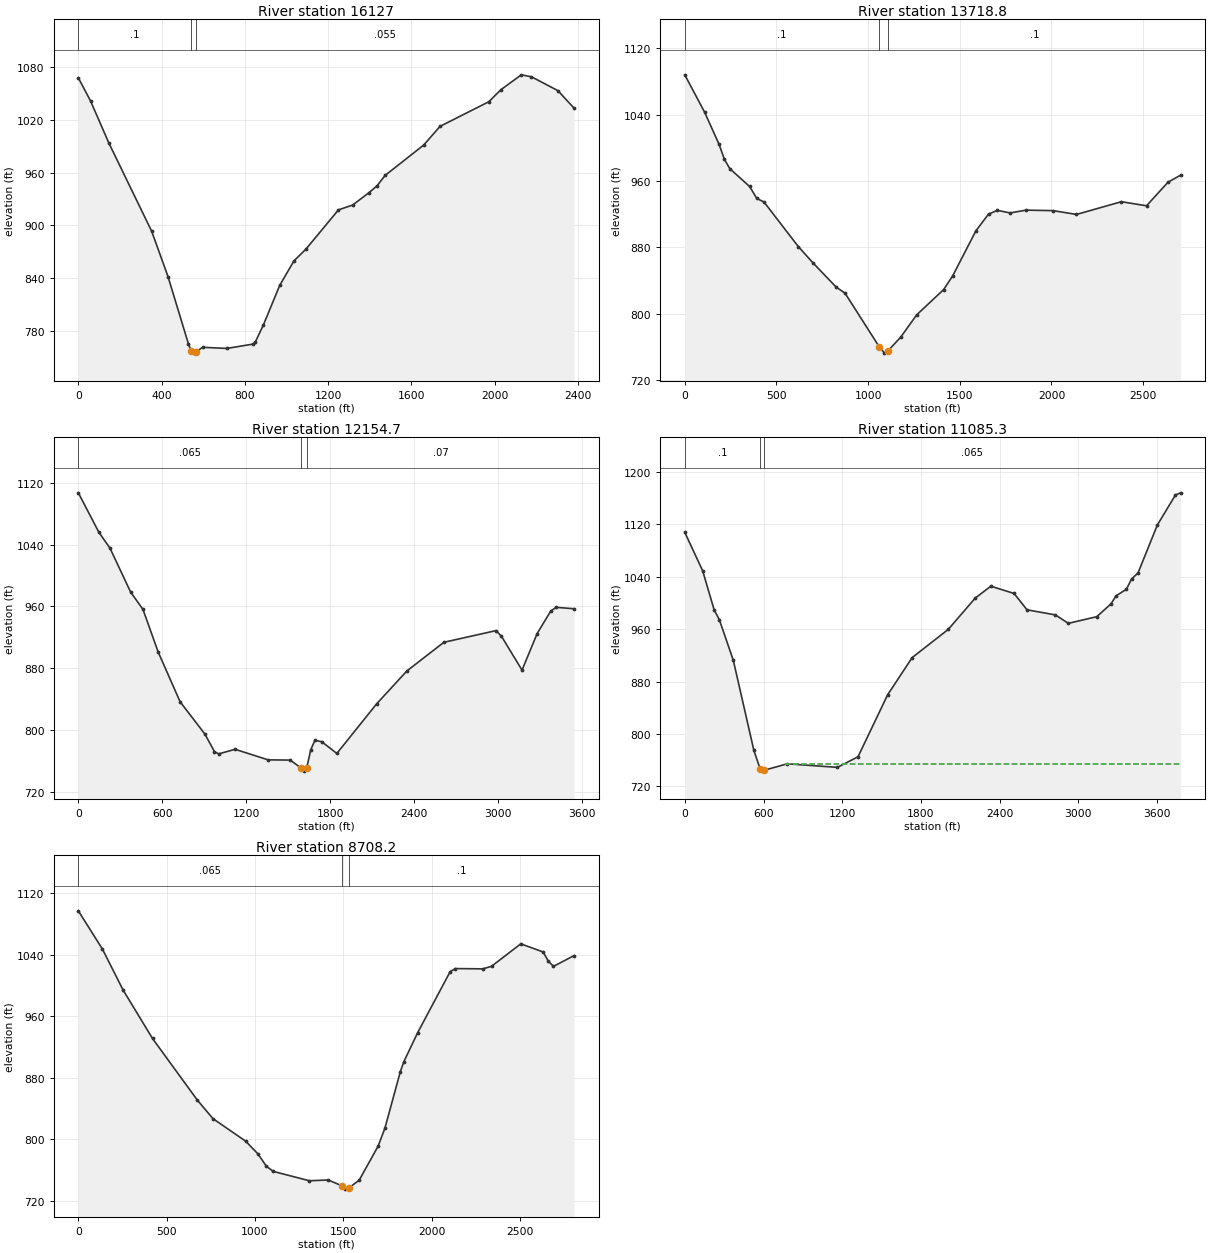
Type RM Length L Ch R = 1 ,16127   ,2414.7,2408.2,2401.1
XS GIS Cut Line= 5
     1553543.437      234221.264     1553173.951      234377.638
     1552978.639      234507.847     1552184.368      234855.069
      1551594.09      235506.111
#Sta/Elev= 30
       0 1067.75    58.7 1041.44   146.8  993.54   352.3  893.37   430.6  841.93
   528.4   765.7  542.25757.1238   557.7  754.86   567.5   756.6   596.8  761.47
   713.9  760.21   840.5   765.2   850.2  767.57   889.2  787.01   967.1  831.75
  1035.3  859.59  1093.7  873.19  1249.6   917.7  1317.7  923.16  1395.7  937.17
  1434.6  944.96  1473.6  956.86    1659  991.36  1737.2 1012.56  1971.5 1040.54
  2030.1 1054.31  2127.7 1071.16  2176.5 1068.94  2303.5 1053.21  2381.6 1033.13
#Mann= 3 , 0 , 0
       0      .1       0  542.25    .045       0   567.5    .055       0
Bank Sta=542.25,567.5
XS Rating Curve= 0 ,0
Exp/Cntr=0.3,0.1

Type RM Length L Ch R = 1 ,13718.8 ,1560.2,1564.1,1567.7
XS GIS Cut Line= 4
     1551839.878      232463.451     1551259.889      233169.305
     1551044.611      233447.083     1550752.944      234856.805
#Sta/Elev= 30
       0 1087.74   108.1 1042.77   186.6 1004.29   216.1  986.05   245.6  974.86
   353.6  953.39   392.9  938.97   432.2  934.72   618.9  881.19   697.5   861.9
   825.2  832.45   874.3  824.98    1060  760.73  1089.3  752.91  1108.8  755.81
  1177.2  771.99    1265  798.98  1411.9  829.37  1460.9  845.73  1588.2  900.13
  1656.7  920.18  1705.7  924.67  1774.2  921.58  1862.4  924.95  2009.3  924.33
  2136.6  919.77  2381.4  935.08  2518.5  930.18    2636   958.6  2704.6  967.02
#Mann= 3 , 0 , 0
       0      .1       0    1060    .045       0  1108.8      .1       0
Bank Sta=1060,1108.8
XS Rating Curve= 0 ,0
Exp/Cntr=0.3,0.1

Type RM Length L Ch R = 1 ,12154.7 ,1067.3,1069.4,1070.9
XS GIS Cut Line= 4
     1551086.277      231822.083     1550016.833      232558.194
     1549614.055      232933.194     1549148.777      234565.138
#Sta/Elev= 30
       0 1106.98   147.5  1055.7   226.2  1035.4   373.8  978.54   462.3  955.97
   570.5  901.05   727.8  836.37   904.9  794.62   973.7  771.81  1003.2   768.9
  1121.3  774.84  1357.3  761.17  1514.5  760.87  1593.1  750.65  1612.8  746.58
  1632.4  750.08  1661.9  774.11  1691.4  786.44  1740.5   784.7  1848.6  769.47
  2133.1  833.72  2348.9   876.2  2613.7  913.41  2986.5  928.55  3025.7  921.27
  3172.8  877.37  3280.8  924.66  3378.8  954.12  3418.1  958.68  3545.6  956.84
#Mann= 3 , 0 , 0
       0    .065       0  1593.1    .045       0  1632.4     .07       0
Bank Sta=1593.1,1632.4
XS Rating Curve= 0 ,0
Exp/Cntr=0.3,0.1

Type RM Length L Ch R = 1 ,11085.3 ,2374.2,2377.1,2378.8
XS GIS Cut Line= 4
     1550537.015      231586.472     1550255.765      231841.681
      1549396.39      232508.347     1547412.015      233695.847
#Sta/Elev= 30
       0 1107.98   136.3 1049.31     224  989.45   262.9  974.88     370  912.46
   526.8  774.89   575.8  746.04   595.4  743.39   605.2  744.73   781.5  754.57
  1163.7  749.14  1320.4   765.3  1546.2  859.89  1733.1   916.7  2008.7  959.87
  2215.3 1007.85  2333.4 1025.78  2510.5 1014.66  2608.9  989.72  2825.4  981.95
  2923.8  969.05  3140.3  979.18  3248.6  998.68  3287.9 1011.07  3366.7 1021.13
    3406 1036.81  3455.2 1045.96  3602.8 1119.32  3740.6 1165.04    3780 1168.36
#Mann= 3 , 0 , 0
       0      .1       0   575.8    .045       0   605.2    .065       0
#XS Ineff= 2 , 0
                          762.79          754.24
Permanent Ineff=
       F       F
Bank Sta=575.8,605.2
XS Rating Curve= 0 ,0
Exp/Cntr=0.3,0.1

Type RM Length L Ch R = 1 ,8708.2  ,1914.4,1907.4,1899.3
XS GIS Cut Line= 5
      1549427.64      230987.514     1548438.057      231539.597
     1548016.833      231835.972     1547669.611      232085.972
     1547151.599      232602.097
#Sta/Elev= 30
       0 1096.81   136.8 1046.88     254  993.58     420  930.82     674  850.64
     762  826.66   947.6  797.27  1015.9  781.03  1064.8   764.7  1103.9  757.99
  1308.1  745.82    1415  746.84  1492.7  739.23  1512.2  734.95  1531.6  736.56
  1589.9   746.5  1696.8  790.55  1735.7   814.1  1823.2  887.67  1842.7   900.5
  1920.5  938.07  2105.3 1017.76  2134.6 1021.71  2290.6 1021.36  2339.3 1024.66
  2505.1  1053.9  2631.8 1043.29  2661.1 1031.31  2690.3 1024.58  2807.3 1038.66
#Mann= 3 , 0 , 0
       0    .065       0  1492.7    .045       0  1531.6      .1       0
Bank Sta=1492.7,1531.6
XS Rating Curve= 0 ,0
Exp/Cntr=0.3,0.1