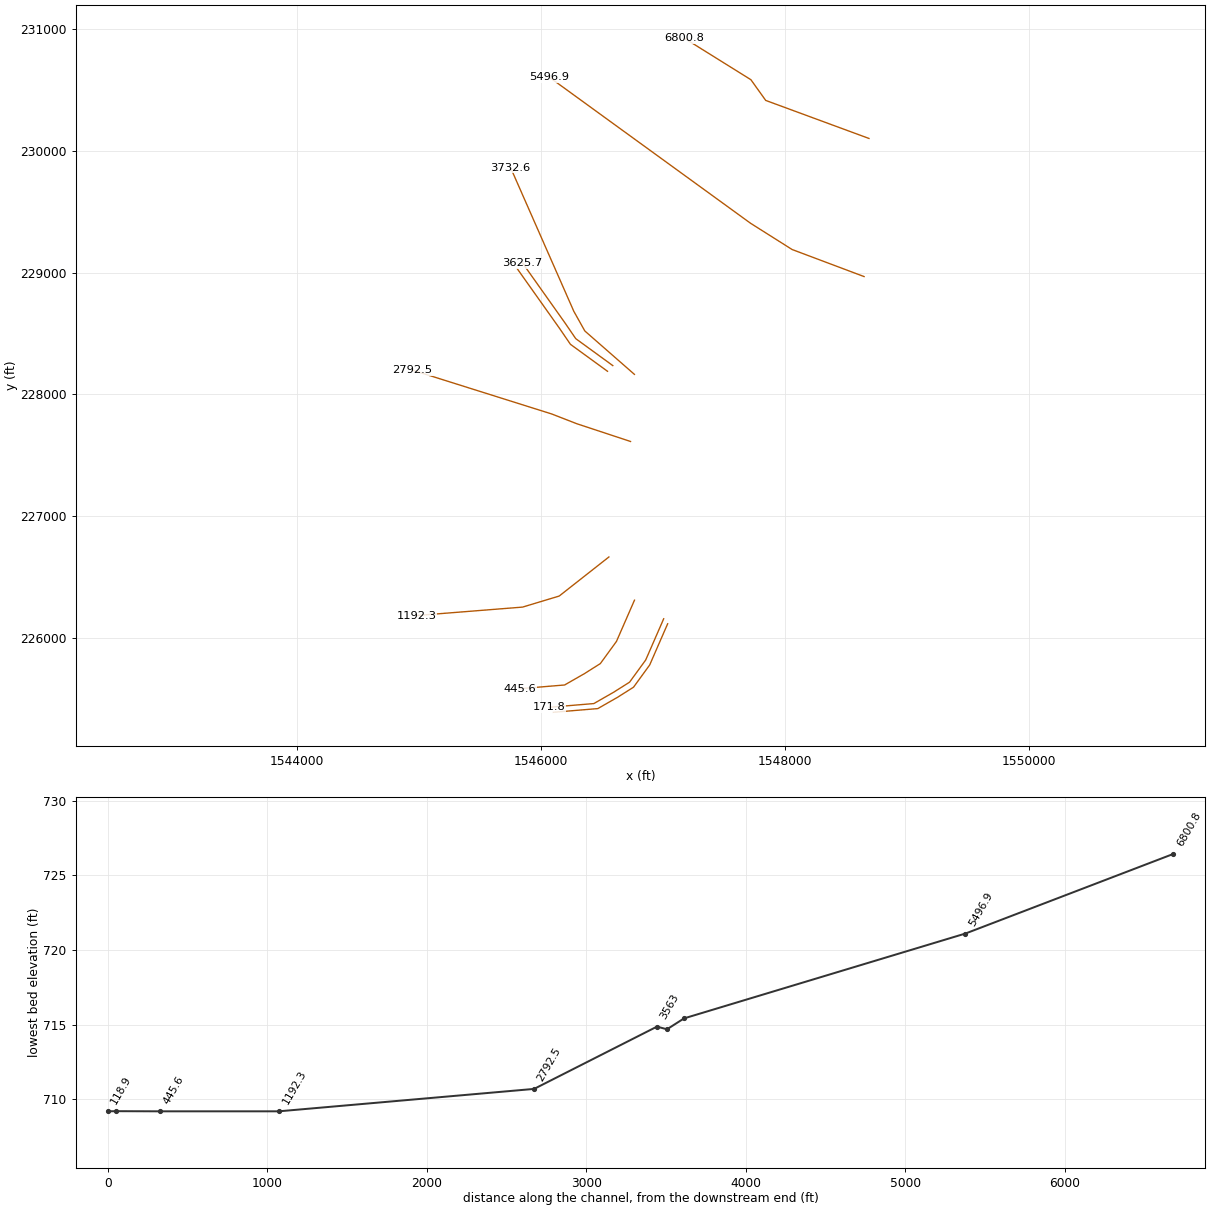
HEC-RAS study SLBCR.prj: SLBCR

--- SLBCR.g01 (geometry) --- (continued)

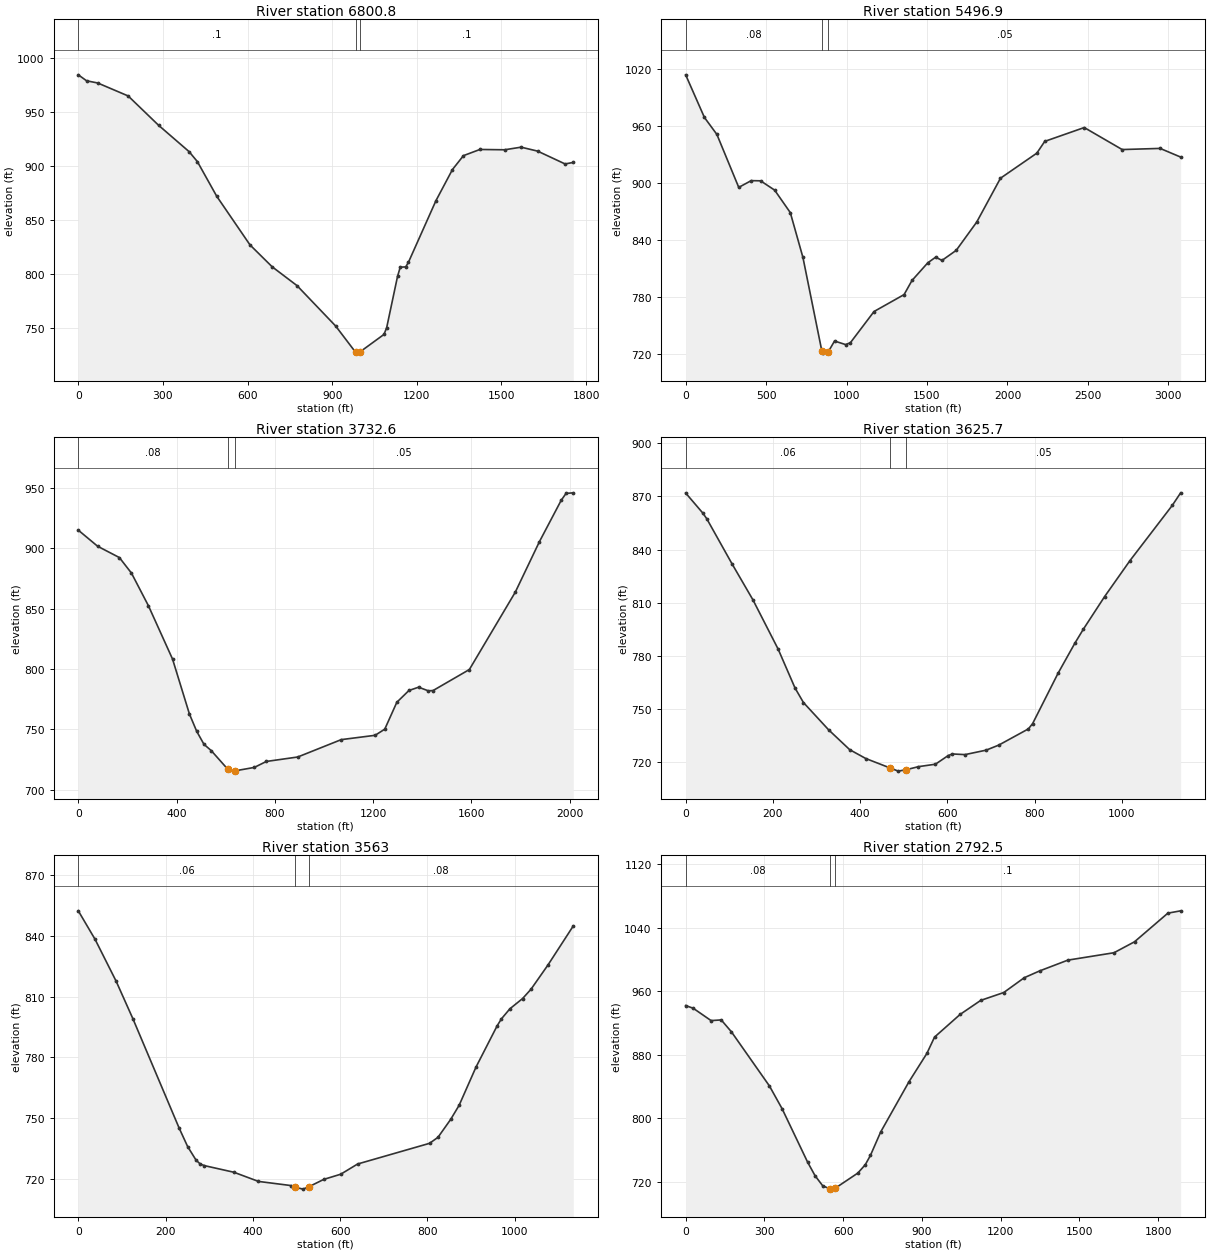
Type RM Length L Ch R = 1 ,6800.8  ,1295.5,1303.9,1312.2
XS GIS Cut Line= 4
      1548689.13      230102.506     1547841.908      230415.006
      1547720.38      230585.144     1547175.241      230925.422
#Sta/Elev= 30
       0  983.97    29.4  978.45    68.7  976.43   176.7  964.43   284.6  937.29
   392.6  912.93   422.1  903.68   490.8  871.57   608.6   826.6   687.1  806.35
   775.4  788.89   912.5  751.46   983.1  727.18   988.6  726.43   998.1  727.48
  1083.6  743.74  1093.1  749.92  1131.6  797.37  1141.3  805.98  1160.8  806.23
  1170.5   810.6  1267.9  867.56  1326.3  896.31  1365.3  909.18  1423.7   914.9
  1511.3  914.61  1569.7  917.02  1628.2  913.37  1725.5  901.51  1754.7   902.9
#Mann= 3 , 0 , 0
       0      .1       0   983.1    .045       0   998.1      .1       0
Bank Sta=983.1,998.1
XS Rating Curve= 0 ,0
Exp/Cntr=0.3,0.1

Type RM Length L Ch R = 1 ,5496.9  ,1774.9,1764.3,1752.9
XS GIS Cut Line= 4
     1548648.777      228967.916       1548058.5      229190.138
     1547718.222      229405.416     1546065.444      230606.805
#Sta/Elev= 30
       0 1013.41   116.4   968.7   194.1   950.8   329.9   895.2   407.5  902.28
   465.8  902.08   553.1   892.3   650.4  868.68   728.9  821.61   846.8     723
   856.6   721.1   886.1  722.44   925.4   733.8   994.1  730.08  1023.6  731.97
  1170.9  764.82  1357.6  782.58  1406.7  797.39  1504.9  815.96    1554  821.89
  1593.3  818.48  1681.7  829.06  1809.4  858.84  1956.8  904.82  2182.7  931.14
  2231.8   943.5  2477.4  958.04  2713.2  934.92    2949  936.12  3076.7  927.02
#Mann= 3 , 0 , 0
       0     .08       0   846.8    .045       0   886.1     .05       0
Bank Sta=846.8,886.1
XS Rating Curve= 0 ,0
Exp/Cntr=0.3,0.1

Type RM Length L Ch R = 1 ,3732.6  ,104.9,107,108.9
XS GIS Cut Line= 4
     1546765.097      228164.531     1546358.196      228521.085
     1546267.918      228682.543     1545749.472      229862.447
#Sta/Elev= 30
       0  914.84    78.7  901.52   167.2  892.16   216.4  879.31   285.3  852.35
   383.6  808.16   452.5  762.61     482  748.36   511.5  737.62     541  732.42
   609.2  716.83   628.6  715.42   638.4  715.67   716.3  718.48   765.4  723.42
   893.2  727.11  1070.3  741.49  1208.1  745.06  1247.4  750.14  1296.6   772.4
  1345.8  782.15  1385.2  784.88  1424.5  781.88  1444.2  782.12  1591.8   799.5
  1778.7  863.53    1877  905.34  1965.6  939.56  1985.3  945.26  2014.8  945.73
#Mann= 3 , 0 , 0
       0     .08       0   609.2    .045       0   638.4     .05       0
Bank Sta=609.2,638.4
XS Rating Curve= 0 ,0
Exp/Cntr=0.3,0.1

Type RM Length L Ch R = 1 ,3625.7  ,62.6,62.6,62.6
XS GIS Cut Line= 4
      1546587.58      228236.579      1546283.76      228457.934
     1546194.784      228588.142     1545847.562      229078.593
#Sta/Elev= 30
       0  871.95    38.6  860.81    48.2  857.47     106  832.01   154.2  811.53
     212  783.66   250.6  761.72   269.9  753.49   327.7  738.03   375.9  726.83
     413   721.8   468.7  716.46   487.2  714.69   505.8  715.51   533.6  717.22
   572.4   718.6   601.5  723.46   611.2   724.4   640.2  724.03   688.7  726.55
   717.8  729.43   785.6  738.58   795.3  741.61   853.4  769.98   892.2   787.1
   911.6  794.99   960.1  813.35  1018.2  833.68  1115.2  864.92  1134.5  872.05
#Mann= 3 , 0 , 0
       0     .06       0   468.7     .04       0   505.8     .05       0
Bank Sta=468.7,505.8
XS Rating Curve= 0 ,0
Exp/Cntr=0.3,0.1

Type RM Length L Ch R = 1 ,3563    ,756.3,770.5,784.9
XS GIS Cut Line= 4
     1546544.177      228189.921     1546240.357      228411.276
     1546151.382      228541.484     1545804.159      229031.935
#Sta/Elev= 30
       0   852.4    38.6  838.26    86.8  817.59   125.3     799   231.3  744.96
   250.6  735.91   269.9   729.2   279.5  727.28   289.2  726.48   356.6  723.21
     413  718.68   487.2  716.64   496.5  715.83   515.1  714.87  528.63716.0703
   562.7  719.69   601.5  722.24   640.2  727.29     805   737.5   824.4  740.48
   853.4  749.31   872.8  756.28   911.6  775.22   960.1  795.63   969.8  799.02
   989.2  803.99  1018.2  809.04  1037.6  813.66  1076.4  825.62  1134.5  844.95
#Mann= 3 , 0 , 0
       0     .06       0   496.5    .045       0  528.63     .08       0
Bank Sta=496.5,528.63
XS Rating Curve= 0 ,0
Exp/Cntr=0.3,0.1

Type RM Length L Ch R = 1 ,2792.5  ,1583.6,1600.2,1613.8
XS GIS Cut Line= 4
     1546732.979      227613.316     1546292.007      227759.149
     1546087.145       227839.01     1544941.312      228200.121
#Sta/Elev= 30
       0  942.03      29  938.56    96.8  923.05   135.5   923.9   174.2  908.97
   319.3   840.6   367.7   811.8   464.5  744.74   493.1  727.52   521.8  715.03
   550.5  710.81   560.1   710.7   569.6  711.83   655.7  730.89   684.3  741.47
   703.9  753.22   742.9   782.7   850.4  845.84   918.8  881.62   948.1  902.26
  1045.7  930.87  1123.9  948.49  1211.8  958.42  1289.9  977.09  1348.5  985.65
    1456  999.24  1631.8 1008.56  1709.9 1022.35  1836.9 1058.42  1885.7 1061.36
#Mann= 3 , 0 , 0
       0     .08       0   550.5    .045       0   569.6      .1       0
Bank Sta=550.5,569.6
XS Rating Curve= 0 ,0
Exp/Cntr=0.3,0.1

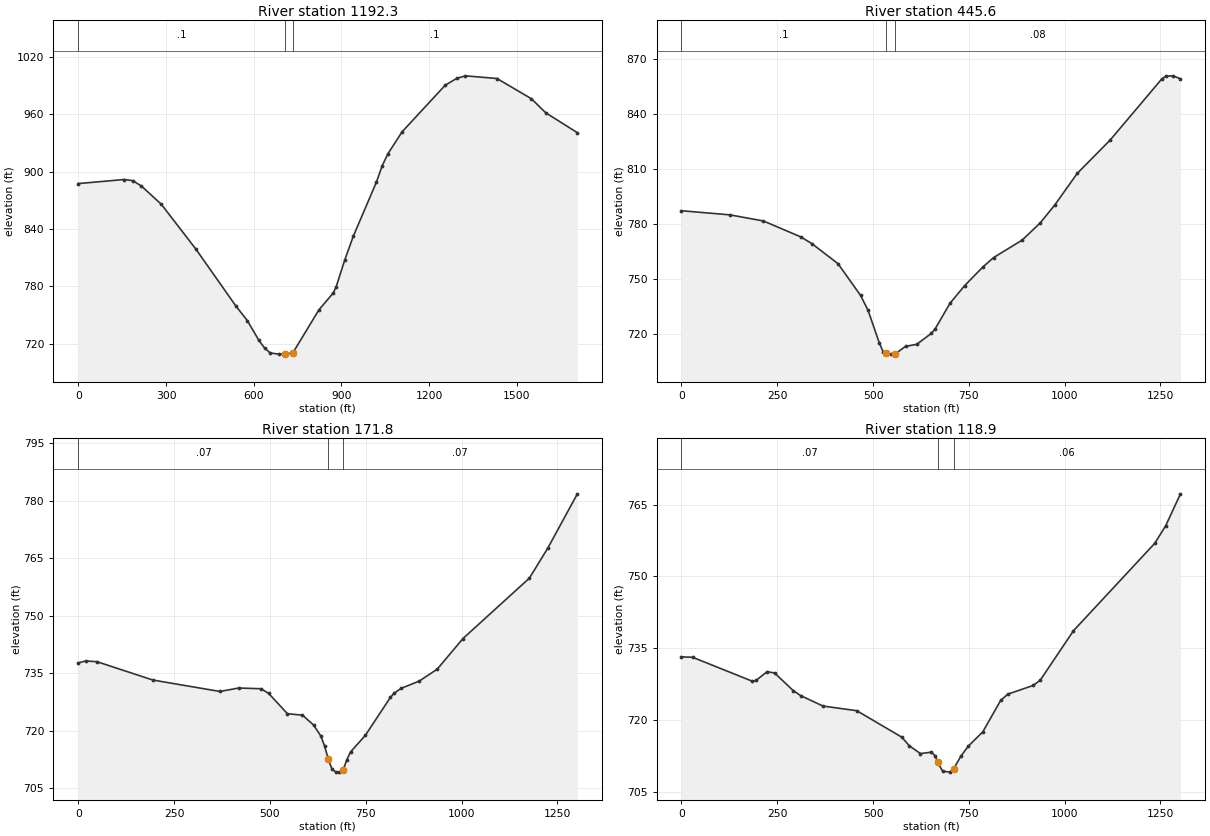
Type RM Length L Ch R = 1 ,1192.3  ,731.7,746.6,761.6
XS GIS Cut Line= 4
     1546555.895      226664.531     1546147.909       226343.35
     1545847.562      226252.638     1544976.034      226183.194
#Sta/Elev= 30
       0  887.68   156.8  891.93   186.1  890.71   215.5  885.16   284.1  865.91
   401.7  819.24   538.8  759.61   578.1  744.32   617.3  723.73   636.9  715.72
   656.5  710.42   685.9   709.2   705.5   709.2   733.6  710.39   823.2  755.61
   872.3  773.29   882.1  779.73   911.6  807.88     941  832.84  1019.6   889.1
  1039.3  906.17  1058.9  918.79    1108  941.99  1255.4  990.69  1294.7  997.76
  1324.2 1000.43  1432.2  997.62  1550.1  976.42  1599.2  961.72  1707.3  940.91
#Mann= 3 , 0 , 0
       0      .1       0   705.5    .045       0   733.6      .1       0
Bank Sta=705.5,733.6
XS Rating Curve= 0 ,0
Exp/Cntr=0.3,0.1

Type RM Length L Ch R = 1 ,445.6   ,282.5,273.8,264.9
XS GIS Cut Line= 6
     1546765.531      226309.496     1546617.961      225970.954
     1546485.583      225788.663     1546355.375      225706.197
     1546192.614      225612.881     1545828.031        225582.5
#Sta/Elev= 30
       0  787.36   126.3  785.12   213.8  781.78     311  773.15   340.2  769.46
   408.5  758.51   467.3  741.24   486.8  733.14   516.2  715.39     526   710.6
  532.86  709.69   545.6   709.2   558.3   709.4   584.8  713.45   613.9  714.52
   652.4  720.56     662  722.95   700.6  736.87   739.1  746.56   786.2  756.63
   814.4  761.81   889.4  771.39   936.3  780.74   974.8  790.66  1032.6  807.66
  1119.3  826.02    1254  859.35  1263.7  860.65  1282.9   860.9  1302.2  859.24
#Mann= 3 , 0 , 0
       0      .1       0  532.86    .045       0   558.3     .08       0
Bank Sta=532.86,558.3
XS Rating Curve= 0 ,0
Exp/Cntr=0.3,0.1

Type RM Length L Ch R = 1 ,171.8   ,52.9,52.9,53.1
XS GIS Cut Line= 6
     1547005.114      226156.718     1546857.545      225818.177
     1546725.166      225635.885     1546594.958       225553.42
     1546432.198      225460.104     1546067.614      225429.722
#Sta/Elev= 30
       0   737.7    19.4  738.19    48.6     738   194.4  733.22   369.3  730.24
   418.3  731.14     477  730.95   496.6  729.73   545.6  724.44   584.8  724.07
   613.9  721.48   633.1  718.57   642.8  715.92   652.4  712.52     662  709.99
   671.7  709.25   681.3  709.21   690.9  709.79   700.6  712.44   710.2  714.47
   748.7  718.77   814.4  728.71   823.8  729.77   842.5  731.07   889.4  732.94
   936.3  736.04  1003.7  744.04    1177  759.79  1225.2  767.65  1302.2  781.77
#Mann= 3 , 0 , 0
       0     .07       0   652.4    .045       0   690.9     .07       0
Bank Sta=652.4,690.9
XS Rating Curve= 0 ,0
Exp/Cntr=0.3,0.1

Type RM Length L Ch R = 1 ,118.9   ,121.8,118.9,116
XS GIS Cut Line= 6
     1547037.666      226115.486     1546890.097      225776.944
     1546757.718      225594.652      1546627.51      225512.187
      1546464.75      225418.871     1546100.166      225388.489
#Sta/Elev= 30
       0  733.24    29.2  733.15   184.6  728.17   194.4  728.31   223.5  730.15
     243  729.88   291.6  726.21     311  725.16   369.3  722.98   457.5  722.01
     575  716.49   594.6   714.7   623.5  713.07   652.4  713.36     662  712.59
  668.43711.3106   681.3  709.41   700.6   709.2   710.2  709.88   729.4  712.56
   748.7  714.63   786.2  717.58   833.2  724.18   851.9  725.47   917.6  727.27
   936.3  728.37    1023  738.69  1234.8  756.89  1263.7  760.59  1302.2  767.24
#Mann= 3 , 0 , 0
       0     .07       0  668.43    .045       0   710.2     .06       0
Bank Sta=668.43,710.2
XS Rating Curve= 0 ,0
Exp/Cntr=0.3,0.1

Chan Stop Cuts=-1
Use User Specified Reach Order=0
Composite Channel Slope=5